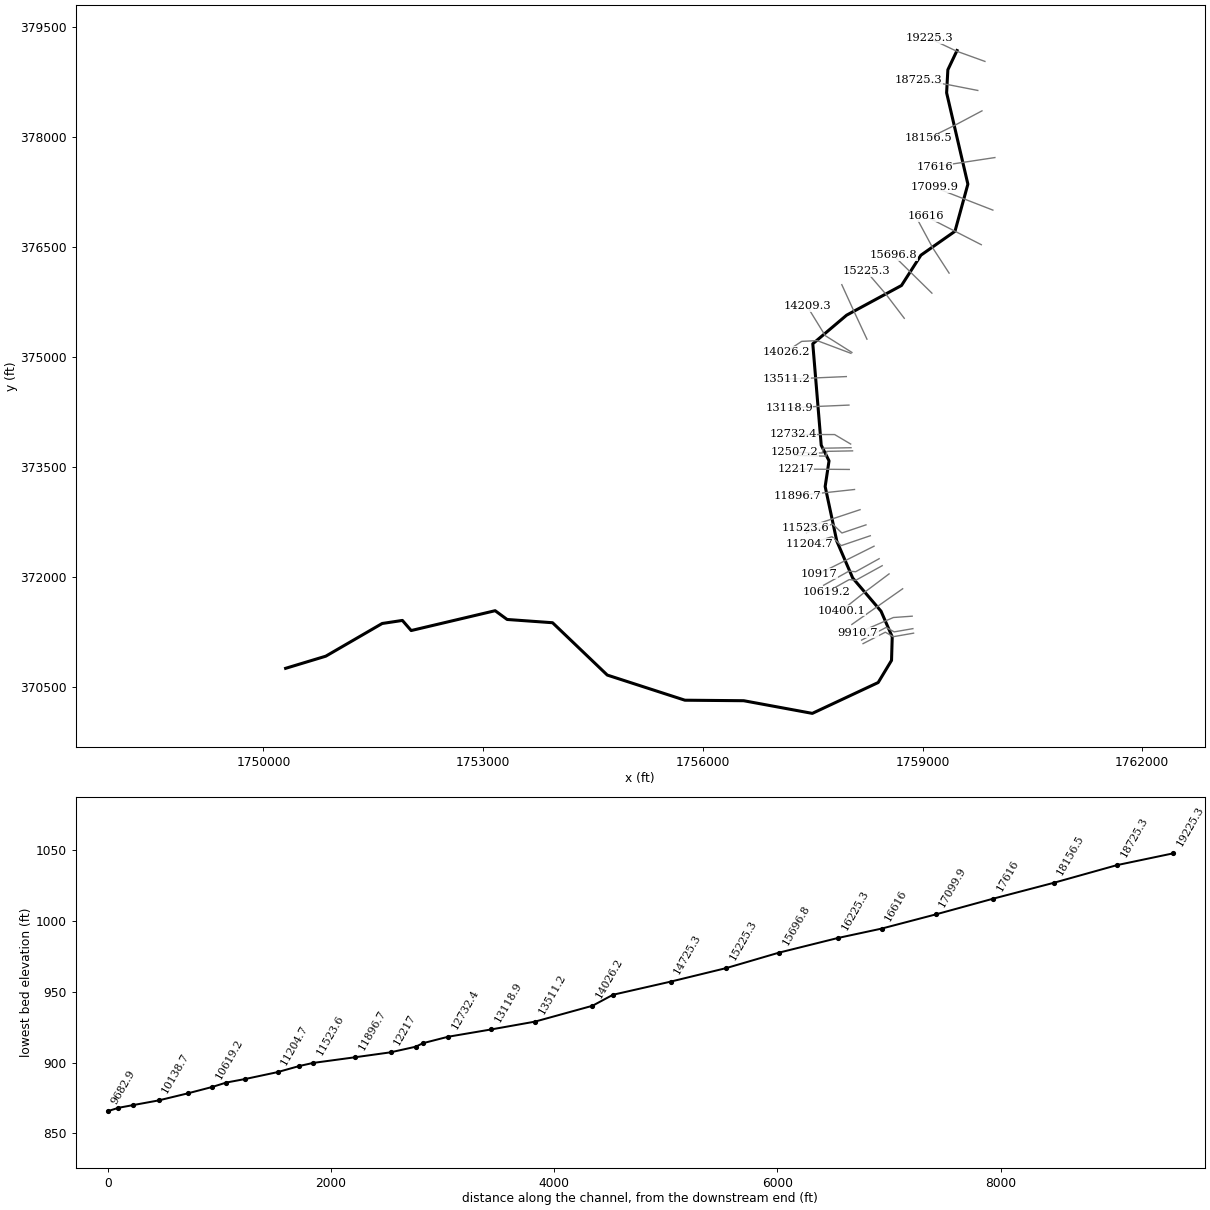
--- ROBINSONCK.prj (project) ---

Proj Title=ROBINSONCK
Current Plan=p01
Default Exp/Contr=0,0
English Units
Geom File=g01
Flow File=f01
Plan File=p01
BEGIN DESCRIPTION:
END DESCRIPTION:
DSS Export Rating Curves= 0
DSS Export Rating Curve Sorted= 0
DSS Export Volume Flow Curves= 0
DXF OffsetX= 0
DXF OffsetY= 0
DXF ScaleX= 0
DXF ScaleY= 0

--- ROBINSONCK.p01 (plan) ---

Plan Title=Floodplain
Program Version=4.00
Geom File=g01
Flow File=f01
K Sum by GR=0
Std Step Tol=0.01
Critical Tol=0.01
Num of Std Step Trials=20
Max Error Tol=0.3
Flow Tol Ratio=0.001
Split Flow NTrial=30
Split Flow Tol=0.02
Split Flow Ratio=0.02
Log Output Level=0
Friction Slope Method=1
Unsteady Friction Slope Method=2
Unsteady Bridges Friction Slope Method=1
Global Log Level=0
CheckData=False
Run HTab=0
Run UNet=0
Run PostProcess=0
UNET Theta=0
UNET Theta Warmup=0
UNET ZTol=0
UNET ZSATol=0
UNET MxIter=0
UNET MaxInSteps=0
UNET DtIC=0
UNET DtMin=0
UNET MaxCRTS=0
UNET WFStab=0
UNET SFStab=0
UNET WFX=0
UNET SFX=0
UNET DSS MLevel=0
UNET DZMax Abort=0
UNET Convert EG Bridges=0
UNET Use Existing IB Tables=0
UNET Froude Limit=0
UNET Froude Power=0
Write IC File=0
Echo Input=False
Echo Output=False
Write Detailed=0

--- ROBINSONCK.f01 (steady flow) ---

Flow Title=NFF Regression Equation
Program Version=4.00
Number of Profiles=1
Profile Names=P100yr
River Rch & RM=ROBINSONCK,Main      ,19225.3
888.0779
River Rch & RM=ROBINSONCK,Main      ,17616
931.6253
River Rch & RM=ROBINSONCK,Main      ,14725.3
1019.935
River Rch & RM=ROBINSONCK,Main      ,13511.2
1307.964
River Rch & RM=ROBINSONCK,Main      ,10917
1382.772
River Rch & RM=ROBINSONCK,Main      ,9910.7
1567.512
River Rch & RM=ROBINSONCK,Main      ,9405.1
1572.000
River Rch & RM=ROBINSONCK,Main      ,8502
1755.260
River Rch & RM=ROBINSONCK,Main      ,3548.3
1928.946
River Rch & RM=ROBINSONCK,Main      ,2938.3
2158.337
River Rch & RM=ROBINSONCK,Main      ,925.2
2205.161
Boundary for River Rch & Prof#=ROBINSONCK,Main      ,1
Up Type=0
Dn Type=3
Dn Slope=0.008841

--- ROBINSONCK.g01 (geometry) ---

Geom Title=USGS 10m DEM
Program Version=4.10

River Reach=ROBINSONCK      ,Main
Reach XY= 30
     1759470.756      379179.445     1759345.769      378916.777
     1759328.834      378602.646     1759619.198      377356.205
     1759442.983      376713.176     1758977.705      376386.788
     1758712.948      375973.593     1757962.948      375568.211
     1757501.533      375177.745     1757616.594        373794.6
     1757723.365      373580.885     1757670.413      373230.277
     1757829.268      372485.572     1758046.281      371982.187
     1758433.434      371528.888     1758586.212      371178.888
     1758576.664      370857.794     1758394.372      370555.711
     1757495.066      370134.791     1756558.434      370307.534
     1755755.483      370314.479     1754695.587       370657.36
     1753948.191       371371.77     1753327.805      371416.185
     1753164.337      371535.833     1752017.636      371264.999
     1751897.844       371403.02     1751621.802      371361.353
     1750851.837       370915.26     1750303.226      370749.461

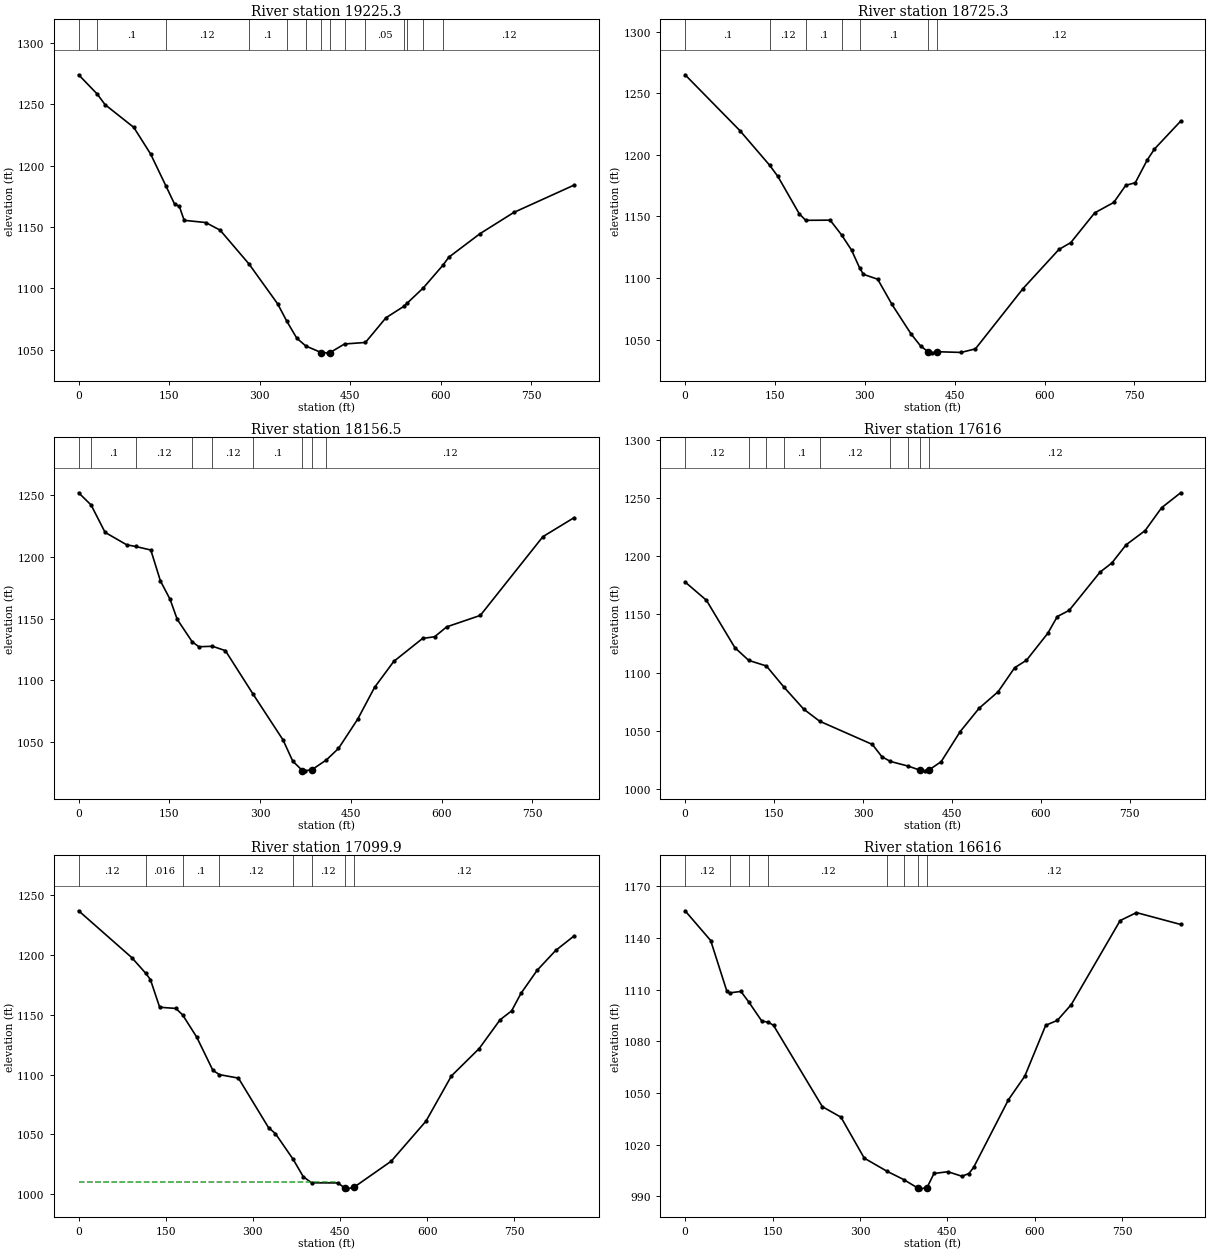
Type RM Length L Ch R = 1 ,19225.3 ,496.1,500,505.7
XS GIS Cut Line= 3
     1759852.144       379031.09      1759467.36      379170.039
     1759095.083      379345.954
#Sta/Elev= 30
       0 1274.24   30.961258.418    43.7 1249.92    91.4  1231.3   119.2 1209.62
  144.241183.902   158.9 1168.78   166.8  1166.9   174.8 1155.51   210.5  1153.7
   234.3 1147.52  282.181119.902   329.7 1087.34  344.981073.038   361.4 1059.34
  376.381052.975   401.6 1047.68   413.1 1047.41   416.6 1047.68   440.4 1054.63
  475.091055.886     509    1076   538.41085.256  544.231087.958  571.071100.471
  603.731119.082     613 1125.36     665 1144.68   720.9 1161.96   820.8 1184.27
#Mann= 14 ,-1 , 0
       0      .1       0   30.96      .1       0  144.24     .12       0
  282.18      .1       0  344.98     .12       0  376.38     .06       0
   401.6    .045       0   416.6     .06       0   440.4      .1       0
  475.09     .05       0   538.4     .12       0  544.23     .05       0
  571.07     .06       0  603.73     .12       0
Bank Sta=401.6,416.6
XS Rating Curve= 0 ,0
Exp/Cntr=0.3,0.1

Type RM Length L Ch R = 1 ,18725.3 ,553.4,568.8,583.3
XS GIS Cut Line= 3
     1759754.736        378634.8     1759349.577      378714.016
     1758940.128      378777.767
#Sta/Elev= 30
       0 1265.03    91.3 1219.76  141.091191.573   154.8 1182.51   190.5 1152.18
  201.281146.816   242.1 1146.95  261.471134.786   277.9 1122.56  291.571107.902
   297.7 1102.94   321.5 1098.96   345.4 1078.44   377.1 1054.57     393 1044.82
   405.3 1040.17   412.8 1039.17   420.3 1040.09   460.6  1039.5   484.6 1042.38
   564.2 1091.43     624 1123.13   643.9 1128.75   683.8 1152.89   715.6 1161.34
   735.6 1175.25   751.5 1177.34   771.4  1195.8   783.4 1204.66   827.2 1227.35
#Mann= 7 ,-1 , 0
       0      .1       0  141.09     .12       0  201.28      .1       0
  261.47     .12       0  291.57      .1       0   405.3    .045       0
   420.3     .12       0
Bank Sta=405.3,420.3
XS Rating Curve= 0 ,0
Exp/Cntr=0.3,0.1

Type RM Length L Ch R = 1 ,18156.5 ,548,540.5,532.7
XS GIS Cut Line= 3
     1759811.689      378356.367     1759449.899      378164.347
      1759082.52      377983.401
#Sta/Elev= 30
       0 1251.84   20.621241.942    43.7 1219.79    79.5 1209.69   94.311208.347
   119.3 1205.49   135.2 1180.44   151.1 1165.61     163  1149.3  187.821131.106
   198.8 1127.15  221.251127.538   242.6 1123.98  288.131088.948     338 1051.56
   353.9 1034.52   369.8  1026.9   373.8 1026.65   385.7  1027.6  409.311035.397
   429.5 1044.76   461.3 1068.51   489.1 1094.19   520.9 1115.26   568.6 1133.89
   588.5 1135.25   608.4 1143.25     664 1152.54   767.4  1216.3   819.1 1231.73
#Mann= 9 ,-1 , 0
       0      .1       0   20.62      .1       0   94.31     .12       0
  187.82      .1       0  221.25     .12       0  288.13      .1       0
   369.8    .045       0   385.7      .1       0  409.31     .12       0
Bank Sta=369.8,385.7
XS Rating Curve= 0 ,0
Exp/Cntr=0.3,0.1

Type RM Length L Ch R = 1 ,17616   ,527.7,516.2,504.2
XS GIS Cut Line= 2
     1759988.163      377719.123     1759161.774      377594.123
#Sta/Elev= 30
       0 1177.86      36 1162.13      84 1121.35  107.311110.467  137.181105.641
  167.051087.302     200 1068.58  226.791058.211   315.9 1038.19   331.9 1027.65
  346.281023.602  376.151019.579   395.9 1016.14   403.9 1015.51   411.9 1016.46
   431.9 1023.38   463.9 1049.19   495.9 1069.32   527.9 1083.49   555.9 1104.18
   575.8 1110.58   611.8 1133.83   627.8 1148.15   647.8 1153.46   699.8  1186.3
   719.8  1194.2   743.8 1209.82   775.8 1221.99   803.8 1241.74   835.8 1254.55
#Mann= 9 ,-1 , 0
       0     .12       0  107.31      .1       0  137.18     .12       0
  167.05      .1       0  226.79     .12       0  346.28      .1       0
  376.15     .12       0   395.9    .045       0   411.9     .12       0
Bank Sta=395.9,411.9
XS Rating Curve= 0 ,0
Exp/Cntr=0.3,0.1

Type RM Length L Ch R = 1 ,17099.9 ,486.7,483.9,480.7
XS GIS Cut Line= 2
     1759960.385      377002.109     1759165.246      377311.137
#Sta/Elev= 30
       0 1237.13    91.7 1197.85  115.741184.686   123.6 1179.49   139.5 1156.39
   167.4 1155.38  179.111149.934   203.3 1131.37   231.2 1103.51  242.491099.966
   275.1 1097.06   326.9 1055.63   338.8  1050.6  369.241029.137   386.7 1014.57
  400.921009.438   446.5 1009.34   458.4 1004.87   462.4 1004.38   474.4 1005.83
   538.2 1027.55     598 1061.05   641.8 1098.91   689.6 1121.83   725.5 1145.84
   745.4 1153.37   761.4 1167.89   789.3 1187.29   821.2 1203.89   853.1 1216.13
#Mann= 8 ,-1 , 0
       0     .12       0  115.74    .016       0  179.11      .1       0
  242.49     .12       0  369.24      .1       0  400.92     .12       0
   458.4    .045       0   474.4     .12       0
#XS Ineff= 2 , 0
          442.78 1009.89
Permanent Ineff=
       F       F
Bank Sta=458.4,474.4
XS Rating Curve= 0 ,0
Exp/Cntr=0.3,0.1

Type RM Length L Ch R = 1 ,16616   ,402.2,390.6,377
XS GIS Cut Line= 2
     1759802.399      376529.887     1759045.455       376917.04
#Sta/Elev= 30
       0 1155.81    43.9 1138.54    71.8 1108.97   76.431108.148    95.8    1109
   109.61102.688   131.7 1091.74  142.781091.145   151.7 1089.28   235.5 1042.08
   267.4    1036   307.4 1012.21  346.55 1004.58     375999.7865   399.2  994.88
   403.2   994.4   415.1  995.15   427.1 1003.33     451 1004.33     475  1001.7
     487  1003.3     495 1006.83   554.8 1046.15   582.8  1059.8   618.7 1089.32
   638.6 1092.18   662.6 1101.36   746.4 1150.12   774.4 1154.75   850.2 1147.87
#Mann= 8 ,-1 , 0
       0     .12       0   76.43    .016       0   109.6      .1       0
  142.78     .12       0  346.55      .1       0     375     .12       0
   399.2    .045       0   415.1     .12       0
Bank Sta=399.2,415.1
XS Rating Curve= 0 ,0
Exp/Cntr=0.3,0.1

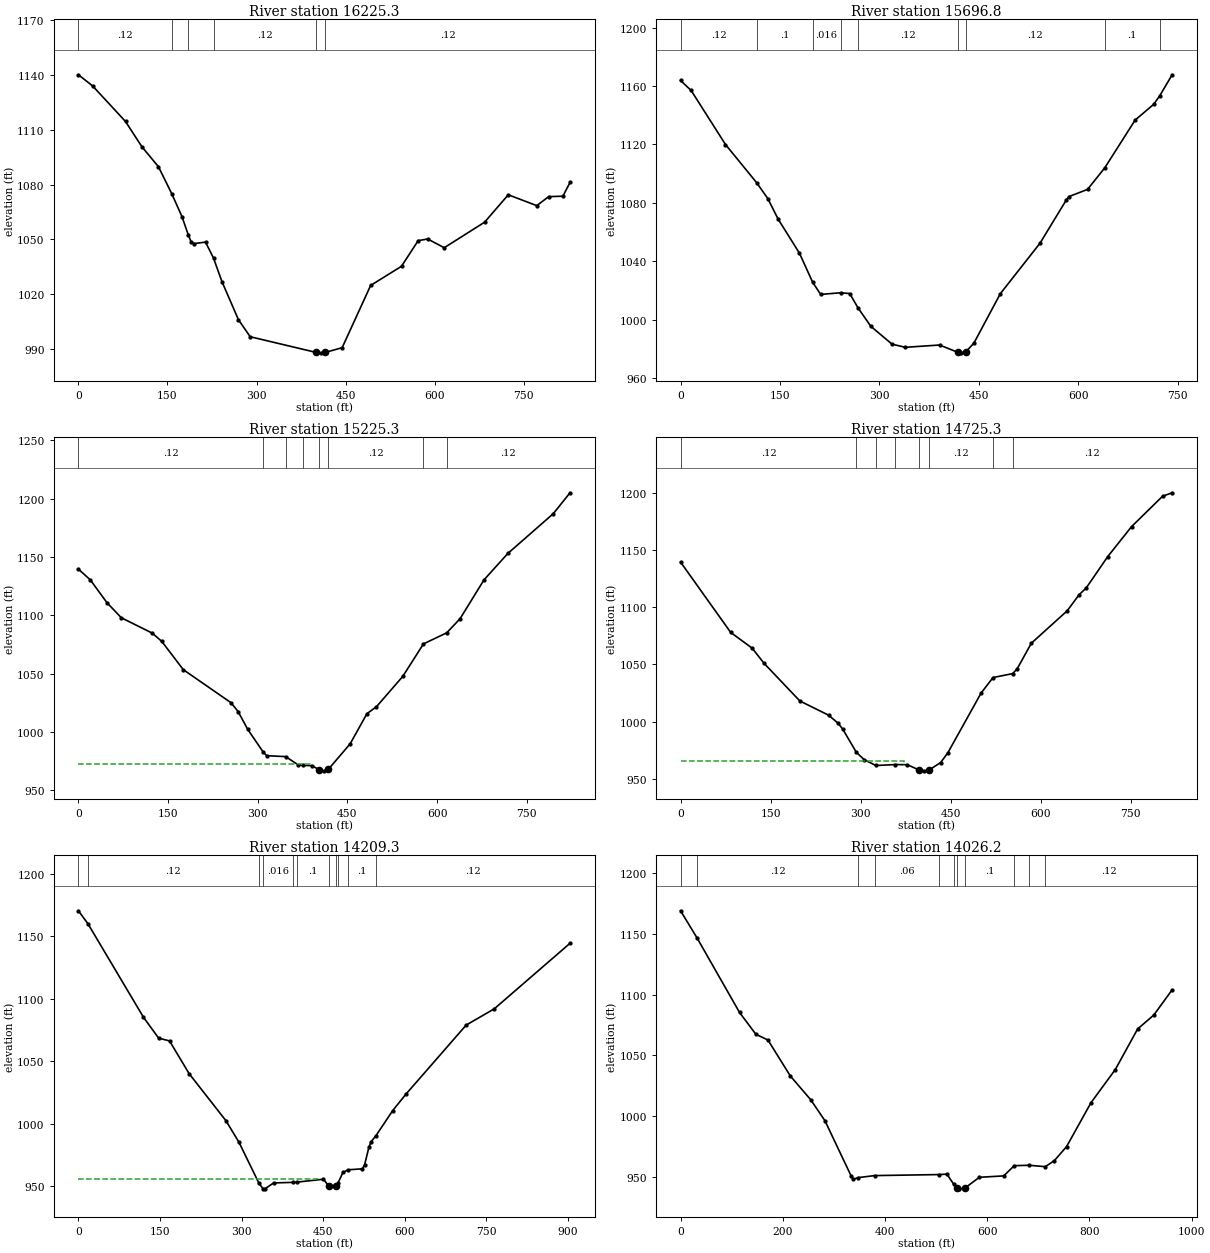
Type RM Length L Ch R = 1 ,16225.3 ,523.4,528.6,536
XS GIS Cut Line= 3
     1759362.695        376142.4     1759140.252      376484.829
     1758941.071      376854.424
#Sta/Elev= 30
       0 1140.15    23.8 1134.07    79.3 1114.56     107 1100.68   134.8 1089.78
  157.161075.025   174.4 1062.47  185.251052.257   190.3 1048.28   194.3 1047.61
   214.1 1048.49  227.611039.687   241.8  1026.8   269.6 1005.94   289.4  996.62
   400.8     988   408.3   987.8   415.8  988.04   444.3  990.62   492.3 1024.72
   544.3 1035.24   572.3 1049.24   588.3  1050.2   616.3 1045.39   684.2 1059.36
   724.2  1074.4   772.2 1068.45   792.2 1073.38   816.2 1073.63   828.2 1081.18
#Mann= 6 ,-1 , 0
       0     .12       0  157.16      .1       0  185.25    .016       0
  227.61     .12       0   400.8    .045       0   415.8     .12       0
Bank Sta=400.8,415.8
XS Rating Curve= 0 ,0
Exp/Cntr=0.3,0.1

Type RM Length L Ch R = 1 ,15696.8 ,474.5,471.4,469.6
XS GIS Cut Line= 2
     1759128.017      375869.013     1758598.503       376388.11
#Sta/Elev= 30
       0 1163.79      16 1156.94    67.8 1119.98   114.71093.903   131.6 1083.01
   147.5 1068.69   179.4  1045.6  199.091025.897   211.3 1017.42  241.281018.542
   255.2 1018.02  267.671008.215     287  995.62   318.9   983.4   338.9  981.24
   390.7   982.8   418.6  977.74   422.6  977.45   430.6  978.26   442.5  984.12
   482.4 1017.96   542.2 1052.46     582 1082.13     586 1084.39   613.9 1089.27
  639.911104.054   685.7 1136.68   713.6 1147.46  722.631153.208   741.5 1167.69
#Mann= 9 ,-1 , 0
       0     .12       0   114.7      .1       0  199.09    .016       0
  241.28      .1       0  267.67     .12       0   418.6    .045       0
   430.6     .12       0  639.91      .1       0  722.63     .12       0
Bank Sta=418.6,430.6
XS Rating Curve= 0 ,0
Exp/Cntr=0.3,0.1

Type RM Length L Ch R = 1 ,15225.3 ,504.7,500,493.5
XS GIS Cut Line= 3
     1758750.656      375525.869     1758501.837      375852.566
     1758233.507      376164.803
#Sta/Elev= 30
       0 1139.55    19.9 1130.31    47.8 1110.74    71.8 1097.83   123.6 1084.64
   139.5 1077.54   175.4 1053.35   255.2 1025.03   267.1 1017.46   283.1 1002.25
  309.52982.3955     315   979.6  346.65978.7737   366.8  971.99  375.12971.2604
   390.7  971.02   403.2  967.37   410.7  966.59   418.2  967.94   454.6  989.76
   482.6 1015.56   498.6  1021.6   542.6 1047.56  577.191075.434  616.13 1084.93
   638.5 1097.05   678.5 1130.36   718.4    1153   794.4  1187.1   822.4 1205.02
#Mann= 8 ,-1 , 0
       0     .12       0  309.52    .016       0  346.65      .1       0
  375.12     .12       0   403.2    .045       0   418.2     .12       0
  577.19      .1       0  616.13     .12       0
#XS Ineff= 2 , 0
          386.69  972.58
Permanent Ineff=
       F       F
Bank Sta=403.2,418.2
XS Rating Curve= 0 ,0
Exp/Cntr=0.3,0.1

Type RM Length L Ch R = 1 ,14725.3 ,513.2,516,519
XS GIS Cut Line= 3
       1758241.1      375240.933     1758067.903      375611.988
     1757897.624      375984.462
#Sta/Elev= 30
       0 1139.38    83.5 1077.95   119.3 1064.16   139.2 1050.88   198.8 1018.02
   246.5 1005.66   262.4  998.64   270.3  993.37  292.85973.2034   306.1  966.68
  325.45 961.685  358.04962.4714   377.7  962.36   397.6   957.7   405.5     957
   413.5  957.53   433.3  964.23   445.3  972.76   500.9 1025.09  520.611038.498
  553.091041.919   560.6 1045.89   584.4 1068.48   644.1 1096.77     664 1110.84
   675.9 1116.78   711.7 1144.16   751.4 1170.36   803.1  1196.9     819 1199.91
#Mann= 8 ,-1 , 0
       0     .12       0  292.85      .1       0  325.45    .016       0
  358.04     .12       0   397.6    .045       0   413.5     .12       0
  520.61      .1       0  553.09     .12       0
#XS Ineff= 2 , 0
          372.55   965.2
Permanent Ineff=
       F       F
Bank Sta=397.6,413.5
XS Rating Curve= 0 ,0
Exp/Cntr=0.3,0.1

Type RM Length L Ch R = 1 ,14209.3 ,158.2,183.1,207.8
XS GIS Cut Line= 3
     1758036.003      375059.985     1757671.419      375289.152
     1757423.155       375691.93
#Sta/Elev= 30
       0 1170.57   17.431160.209   119.6 1085.23   147.5 1068.49   167.5  1066.3
   203.4 1040.11   271.1 1002.41   295.1  985.14   331.4952.6537  339.18947.8988
   342.9  947.75   358.8  952.48  394.68  952.94  401.17953.1103   450.5  955.44
  460.68  949.79     474  949.88  477.55  952.77   486.3  960.87  495.68963.0113
   522.1  963.79     526  966.82     534  980.97     538  985.45  546.94990.3127
   577.7  1010.4   601.6 1023.36   712.9 1078.98   764.6 1092.02   903.8 1144.53
#Mann= 11 ,-1 , 0
       0      .1       0   17.43     .12       0   331.4      .1       0
  339.18    .016       0  394.68     .06       0  401.17      .1       0
  460.68    .045       0     474      .1       0  477.55     .12       0
  495.68      .1       0  546.94     .12       0
#XS Ineff= 2 , 0
          446.77  955.99
Permanent Ineff=
       F       F
Bank Sta=460.68,474
XS Rating Curve= 0 ,0
Exp/Cntr=0.3,0.1

Type RM Length L Ch R = 1 ,14026.2 ,515,515,514.6
XS GIS Cut Line= 4
     1758022.114      375047.833     1757560.308      375221.444
     1757350.239      375211.027     1757134.961      375068.666
#Sta/Elev= 30
       0 1168.99   32.491146.469   115.4 1085.27   147.2 1067.38   171.1  1062.5
   214.8 1032.95   254.6 1013.43   282.5  996.12   334.2  950.21   338.2  947.93
  348.02949.2853  379.62 950.916  505.01951.7536   521.1  952.12  534.58943.7304
     541  940.48     545  940.01   556.9  940.81   584.6  949.52   632.3  950.67
  652.87 959.082  682.44959.4112  713.66958.2532   731.5  963.29   755.3  974.82
     803 1010.91   850.6 1038.26   894.3 1071.66     926 1083.15   961.8 1103.92
#Mann= 11 ,-1 , 0
       0      .1       0   32.49     .12       0  348.02    .016       0
  379.62     .06       0  505.01     .05       0  534.58      .1       0
     541    .045       0   556.9      .1       0  652.87     .12       0
  682.44     .06       0  713.66     .12       0
Bank Sta=541,556.9
XS Rating Curve= 0 ,0
Exp/Cntr=0.3,0.1

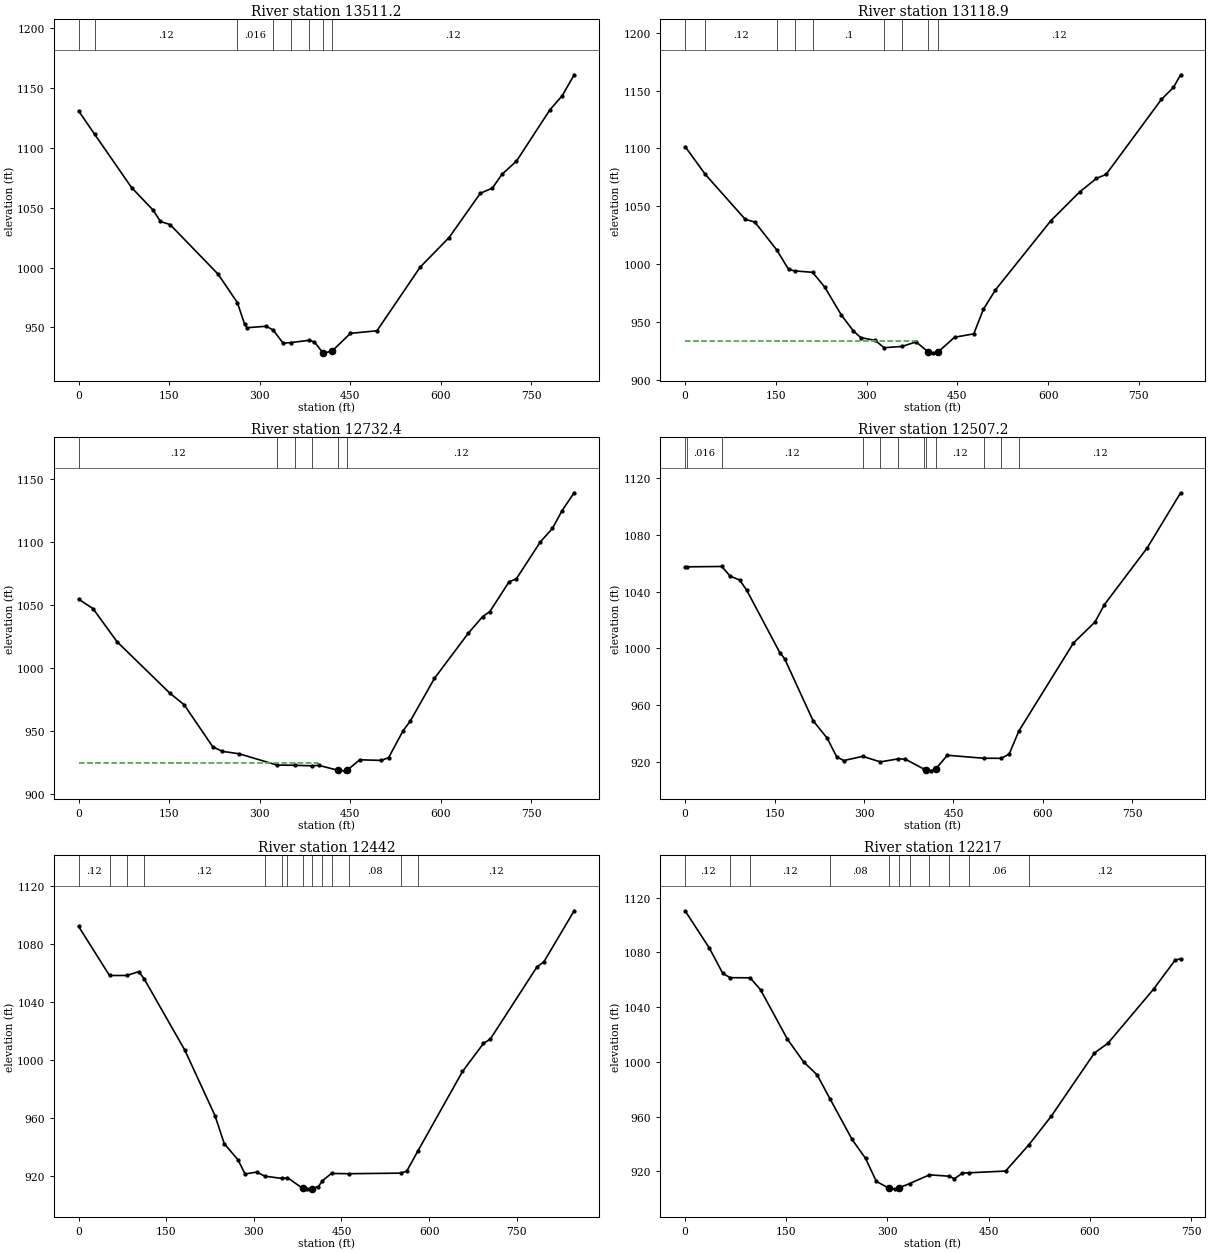
Type RM Length L Ch R = 1 ,13511.2 ,392.2,392.3,392.4
XS GIS Cut Line= 2
     1757959.285      374730.601     1757138.762      374694.925
#Sta/Elev= 30
       0 1130.73   26.681111.194    87.7 1066.83   123.6 1047.87   135.6 1038.48
   151.5 1035.92   231.2  994.48  263.19970.6863   275.1  952.65   279.1   949.8
     311  951.03  322.32947.8855   338.9  936.95  351.88937.3956  381.45939.2664
   390.7  938.01   404.7  928.91   406.7  928.83   419.7  930.14   450.5  945.11
   494.4  947.23   566.1  1000.4     614 1025.09   665.8 1062.06   685.7 1066.35
   701.7 1077.91   725.6  1088.8   781.4  1131.9   801.4 1143.37   821.3 1160.94
#Mann= 8 ,-1 , 0
       0      .1       0   26.68     .12       0  263.19    .016       0
  322.32      .1       0  351.88    .016       0  381.45     .12       0
   404.7    .045       0   419.7     .12       0
Bank Sta=404.7,419.7
XS Rating Curve= 0 ,0
Exp/Cntr=0.3,0.1

Type RM Length L Ch R = 1 ,13118.9 ,387.5,386.5,385.4
XS GIS Cut Line= 3
     1757995.456      374341.533     1757586.337      374323.937
     1757177.354      374303.054
#Sta/Elev= 30
       0  1101.6   33.341077.573    99.4  1038.7   115.3 1036.32  151.591012.163
     171   995.4  181.15994.1318  210.71 992.905   230.6  980.26   258.4  955.87
   278.3  942.12   290.2  936.53   314.1  934.07  328.97927.7779  358.53 928.851
   381.7  932.77   401.4   924.3   409.5  923.32   417.4  923.71   445.3   936.8
   477.1  939.72     493  960.92   512.9   977.7   604.3 1037.38     652 1062.31
   679.9 1074.06   695.8 1077.51   787.2 1142.32   807.1 1152.66     819 1163.61
#Mann= 9 ,-1 , 0
       0      .1       0   33.34     .12       0  151.59      .1       0
  181.15    .016       0  210.71      .1       0  328.97    .016       0
  358.53     .12       0   401.4    .045       0   417.4     .12       0
#XS Ineff= 2 , 0
           381.2  933.38
Permanent Ineff=
       F       F
Bank Sta=401.4,417.4
XS Rating Curve= 0 ,0
Exp/Cntr=0.3,0.1

Type RM Length L Ch R = 1 ,12732.4 ,187.2,225.1,258.2
XS GIS Cut Line= 3
     1758018.822      373810.016     1757800.072      373939.356
     1757233.232      373940.224
#Sta/Elev= 30
       0 1054.71    23.8 1047.24    63.5 1020.94   150.9  980.05   174.7  970.79
   222.4   937.2   238.2  933.65   266.1  931.72  328.35922.7971  357.88922.5601
  387.42922.1558   397.8  922.54     430  918.56   441.7  918.16     445  918.71
   465.7  926.94   501.6  926.46   513.6  928.68   537.6   950.1   549.5   957.8
   589.4  991.64   645.3 1027.47   669.3  1040.8   681.2  1044.8   713.2 1068.57
   725.2  1070.9   765.1 1100.37     785 1110.98     801 1125.21     821 1139.36
#Mann= 6 ,-1 , 0
       0     .12       0  328.35      .1       0  357.88    .016       0
  387.42     .12       0     430    .045       0     445     .12       0
#XS Ineff= 2 , 0
          397.31  924.65
Permanent Ineff=
       F       F
Bank Sta=430,445
XS Rating Curve= 0 ,0
Exp/Cntr=0.3,0.1

Type RM Length L Ch R = 1 ,12507.2 ,69.9,65.2,68.4
XS GIS Cut Line= 4
     1758023.698      373759.914     1757642.448       373752.97
     1757631.336      373687.692     1757248.003       373696.72
#Sta/Elev= 30
       0 1057.33    2.491057.417   61.571057.675    75.5 1050.88    91.4 1048.13
   103.3 1040.95   158.9  996.91   166.8  992.74   214.5  949.05   238.3  936.61
   254.2  923.49   266.1  920.88   297.9  923.83  327.44 919.928  356.98922.0339
   369.4  921.82  400.38914.9025   404.7  914.41   412.5  913.62   420.3  914.84
   439.7  924.61  500.71922.4918  530.26922.4554   543.4  925.42   559.8 941.747
   651.2 1003.72   687.2 1018.43   703.2  1030.8     775 1070.82     831 1109.62
#Mann= 12 ,-1 , 0
       0     .12       0    2.49    .016       0   61.57     .12       0
   297.9      .1       0  327.44    .016       0  356.98     .12       0
  400.38    .016       0   404.7    .045       0   420.3     .12       0
  500.71     .08       0  530.26     .06       0   559.8     .12       0
Bank Sta=404.7,420.3
XS Rating Curve= 0 ,0
Exp/Cntr=0.3,0.1

Type RM Length L Ch R = 1 ,12442   ,258.3,225,188.7
XS GIS Cut Line= 4
     1758044.531      373716.859     1757692.448      373709.914
     1757681.336      373644.637     1757251.475      373655.053
#Sta/Elev= 30
       0 1091.83   52.87 1058.06   82.411058.064   102.9 1060.72  111.951055.909
     182 1006.48   233.4  961.62   249.3  942.26     273  931.02   284.9  921.37
   304.7  922.67  318.74919.8756  348.29918.2834  357.51918.8467   383.3  911.51
   391.1  911.13   398.9  911.29   410.6  912.71  417.43916.7009  432.93921.7474
  462.48 921.545  551.11921.9458   561.7  923.28  580.66937.0699   657.2  991.95
   693.1 1011.26     705 1014.35   784.6 1063.92   796.6 1067.53   848.4 1102.63
#Mann= 14 ,-1 , 0
       0     .12       0   52.87    .016       0   82.41      .1       0
  111.95     .12       0  318.74      .1       0  348.29    .016       0
  357.51     .12       0   383.3    .045       0   398.9     .12       0
  417.43      .1       0  432.93    .016       0  462.48     .08       0
  551.11     .06       0  580.66     .12       0
Bank Sta=383.3,398.9
XS Rating Curve= 0 ,0
Exp/Cntr=0.3,0.1

Type RM Length L Ch R = 1 ,12217   ,317.8,320.3,323
XS GIS Cut Line= 2
     1757999.508      373463.227     1757264.916      373468.653
#Sta/Elev= 30
       0 1110.41    35.9  1083.2    55.9 1064.62   66.921061.517   96.461061.417
   111.8 1052.69   151.7 1016.56   175.7  999.97   195.6  990.54   214.6973.1575
   247.5  943.31   267.5  929.43   283.5  912.64   302.3  907.55   311.4  907.18
   317.3   907.9  332.75911.0037  362.28917.4288  391.82916.3893   399.2  914.53
   411.2  918.71  421.36918.9146   475.1  920.19  509.97939.5846     543   960.4
   606.8 1006.46   626.8 1013.56   694.7 1053.28   726.6 1074.48   734.6 1075.25
#Mann= 11 ,-1 , 0
       0     .12       0   66.92    .016       0   96.46     .12       0
   214.6     .08       0   302.3    .045       0   317.3     .12       0
  332.75      .1       0  362.28    .016       0  391.82     .08       0
  421.36     .06       0  509.97     .12       0
#XS Ineff= 2 , 0
                          496.62          926.71
Permanent Ineff=
       F       F
Bank Sta=302.3,317.3
XS Rating Curve= 0 ,0
Exp/Cntr=0.3,0.1

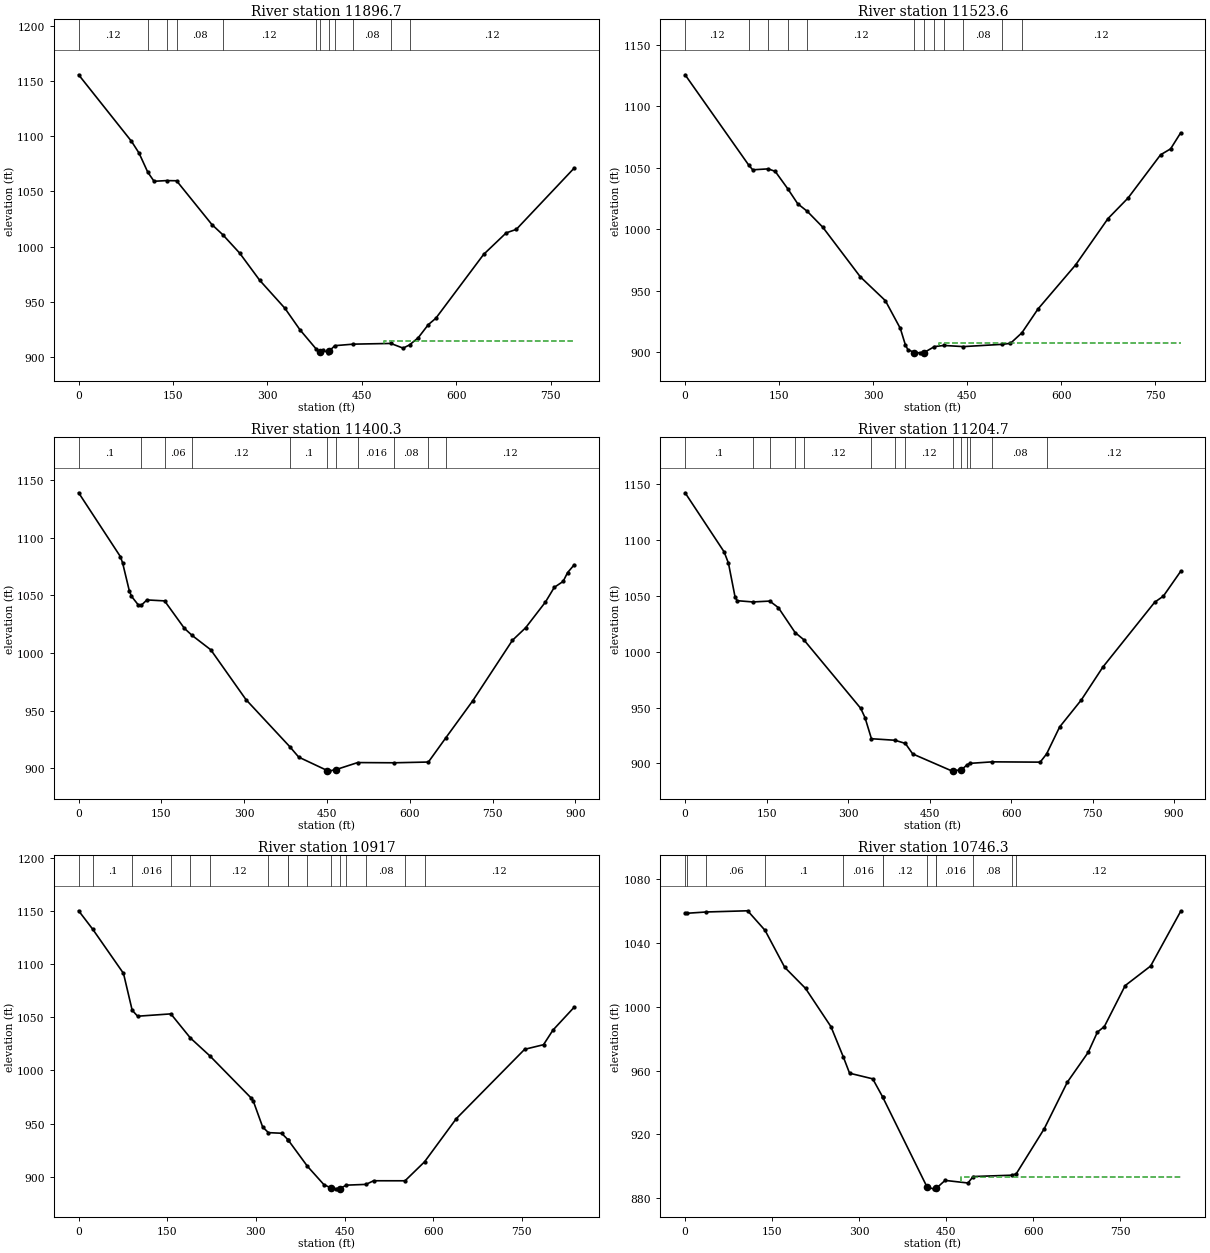
Type RM Length L Ch R = 1 ,11896.7 ,368.4,373.1,377.7
XS GIS Cut Line= 2
     1758071.468      373189.794     1757288.482      373104.725
#Sta/Elev= 30
       0 1155.75      84 1095.45      96 1084.78  109.991067.338   119.9 1059.21
   139.71059.825  155.661059.659   211.9 1019.92  228.831010.933   255.9  994.12
   287.8  969.45   327.8  944.11   351.8  924.56  377.38907.2674   383.2  904.27
   387.8  906.52   395.8  903.68   398.2  905.16  407.09910.1762   436.8911.5675
  496.22912.1975   515.7  907.94  525.93910.8815   539.7  917.34   555.7   929.2
   567.7     935   643.7  992.92   679.6 1012.45   695.6 1015.59   787.6 1071.16
#Mann= 12 ,-1 , 0
       0     .12       0  109.99    .016       0   139.7     .12       0
  155.66     .08       0  228.83     .12       0  377.38     .08       0
   383.2    .045       0   398.2     .08       0  407.09    .016       0
   436.8     .08       0  496.22     .06       0  525.93     .12       0
#XS Ineff= 2 , 0
                          484.73          914.44
Permanent Ineff=
       F       F
Bank Sta=383.2,398.2
XS Rating Curve= 0 ,0
Exp/Cntr=0.3,0.1

Type RM Length L Ch R = 1 ,11523.6 ,156.4,123.3,86.3
XS GIS Cut Line= 2
     1758146.989      372914.187     1757396.989      372665.489
#Sta/Elev= 30
       0 1125.61  101.431052.253   107.8  1048.4  132.541049.165   143.7 1047.13
  163.661033.043   179.6 1020.82  194.781014.696   219.5 1001.81   279.4  961.46
   319.3  942.13   343.2  919.55   351.2  906.29   355.2   902.3   365.8  899.97
   375.1  899.71   380.8  899.87  397.67904.7857   412.6 905.714  443.72904.7794
  505.95906.6285   518.8  907.41  537.07915.9914   562.7  935.31   622.6  971.07
   674.4 1008.81   706.4 1025.53   758.2 1060.61   774.2 1065.43   790.2 1078.42
#Mann= 12 ,-1 , 0
       0     .12       0  101.43    .016       0  132.54     .12       0
  163.66     .08       0  194.78     .12       0   365.8    .045       0
   380.8     .12       0  397.67      .1       0   412.6    .016       0
  443.72     .08       0  505.95     .06       0  537.07     .12       0
#XS Ineff= 2 , 0
                          404.15          907.42
Permanent Ineff=
       F       F
Bank Sta=365.8,380.8
XS Rating Curve= 0 ,0
Exp/Cntr=0.3,0.1

Type RM Length L Ch R = 1 ,11400.3 ,212.9,195.6,200.4
XS GIS Cut Line= 4
     1758227.843      372707.121      1757898.85       372596.01
     1757772.982      372717.538     1757415.343      372602.086
#Sta/Elev= 30
       0 1139.28    75.8 1083.69    79.8 1078.11    91.8 1054.15    95.8 1049.29
   107.8 1041.97   113.31041.354   123.7 1046.14  155.791045.292   191.6 1021.46
   205.6 1015.29   239.5 1002.77   303.3  959.44  382.49918.6245   398.9  909.46
   450.6   897.8   454.5  897.55   466.5  898.64  505.66904.7376  571.77904.5516
  633.84905.2024  664.88925.9155   714.1  958.38   786.1 1011.02   810.1 1021.96
     846 1044.33     862 1057.08     878 1062.23     886 1069.85     898 1076.64
#Mann= 11 ,-1 , 0
       0      .1       0   113.3    .016       0  155.79     .06       0
   205.6     .12       0  382.49      .1       0   450.6    .045       0
   466.5     .12       0  505.66    .016       0  571.77     .08       0
  633.84     .06       0  664.88     .12       0
Bank Sta=450.6,466.5
XS Rating Curve= 0 ,0
Exp/Cntr=0.3,0.1

Type RM Length L Ch R = 1 ,11204.7 ,234,287.7,322.8
XS GIS Cut Line= 4
     1758286.871      372558.683     1757890.169      372424.135
     1757764.301      372545.663      1757461.35       372448.44
#Sta/Elev= 30
       0 1142.54    71.8 1089.57    79.8 1079.42    91.8 1049.51    95.8 1045.79
  124.62 1044.65  155.81 1045.43   171.6 1039.57  202.46 1017.22  218.191010.897
   323.2  949.27   331.1  940.95  342.94922.0124  386.35920.6313  405.32917.8156
   418.9  908.38   490.5  893.22   493.5  893.36   508.5  894.11  518.99898.6298
  524.19899.9227  565.25901.2844   653.5  901.02   665.3908.3718   689.3  932.55
   729.1  956.72   768.8  986.22   864.3 1044.44   880.2 1049.87     912 1072.05
#Mann= 14 ,-1 , 0
       0      .1       0  124.62    .016       0  155.81     .06       0
  202.46      .1       0  218.19     .12       0  342.94    .016       0
  386.35      .1       0  405.32     .12       0   493.5    .045       0
   508.5     .12       0  518.99     .08       0  524.19    .016       0
  565.25     .08       0   665.3     .12       0
Bank Sta=493.5,508.5
XS Rating Curve= 0 ,0
Exp/Cntr=0.3,0.1

Type RM Length L Ch R = 1 ,10917   ,183.4,170.7,158.1
XS GIS Cut Line= 2
     1758337.944       372416.02     1757587.944       372041.02
#Sta/Elev= 30
       0  1150.6   23.951133.131    75.9 1091.55   90.591056.843    99.8 1051.18
  156.041053.378  189.061030.669  222.081013.754   291.5  974.29   295.5  971.24
   311.4  946.69  321.15941.3937   343.4  940.82  354.17934.7878  354.75 934.289
  387.19909.6484   415.3   892.2   426.6  889.43   435.2   888.4   441.6   888.7
  453.24891.8824  486.26 892.601   499.1  896.02  552.31895.9925  585.33913.8871
   638.9  954.49   754.7 1019.97   786.6  1024.3   802.6 1038.08   838.5 1059.66
#Mann= 16 ,-1 , 0
       0     .12       0   23.95      .1       0   90.59    .016       0
  156.04     .06       0  189.06      .1       0  222.08     .12       0
  321.15    .016       0  354.17     .12       0  354.75      .1       0
  387.19     .12       0   426.6    .045       0   441.6     .12       0
  453.24    .016       0  486.26     .08       0  552.31     .06       0
  585.33     .12       0
Bank Sta=426.6,441.6
XS Rating Curve= 0 ,0
Exp/Cntr=0.3,0.1

Type RM Length L Ch R = 1 ,10746.3 ,125.6,127,123.7
XS GIS Cut Line= 4
      1758407.53      372245.315      1758086.35      372067.364
     1757994.336      372075.176     1757649.718      371883.336
#Sta/Elev= 30
       0 1058.51    2.751058.565   36.511059.375   107.8 1060.13  137.811047.849
   171.6 1024.72   207.5  1011.5   251.4  987.47  272.88968.3313   283.4  958.35
   323.3  954.82  340.41943.4903  340.79943.1606   417.2  886.83   428.8  885.89
   432.6  886.15  432.61886.1529     448  891.18   487.4  889.55  496.44893.5972
  564.05 894.454  570.73895.3826   618.9  923.57   658.7  952.76   694.6  971.42
   710.5  984.11   722.5  987.61   758.3 1013.24   802.2 1025.51   853.9 1059.76
#Mann= 13 ,-1 , 0
       0      .1       0    2.75    .016       0   36.51     .06       0
  137.81      .1       0  272.88    .016       0  340.41      .1       0
  340.79     .12       0   417.2    .045       0   432.6     .12       0
  432.61    .016       0  496.44     .08       0  564.05     .06       0
  570.73     .12       0
#XS Ineff= 2 , 0
                          476.14          893.04
Permanent Ineff=
       F       F
Bank Sta=417.2,432.6
XS Rating Curve= 0 ,0
Exp/Cntr=0.3,0.1

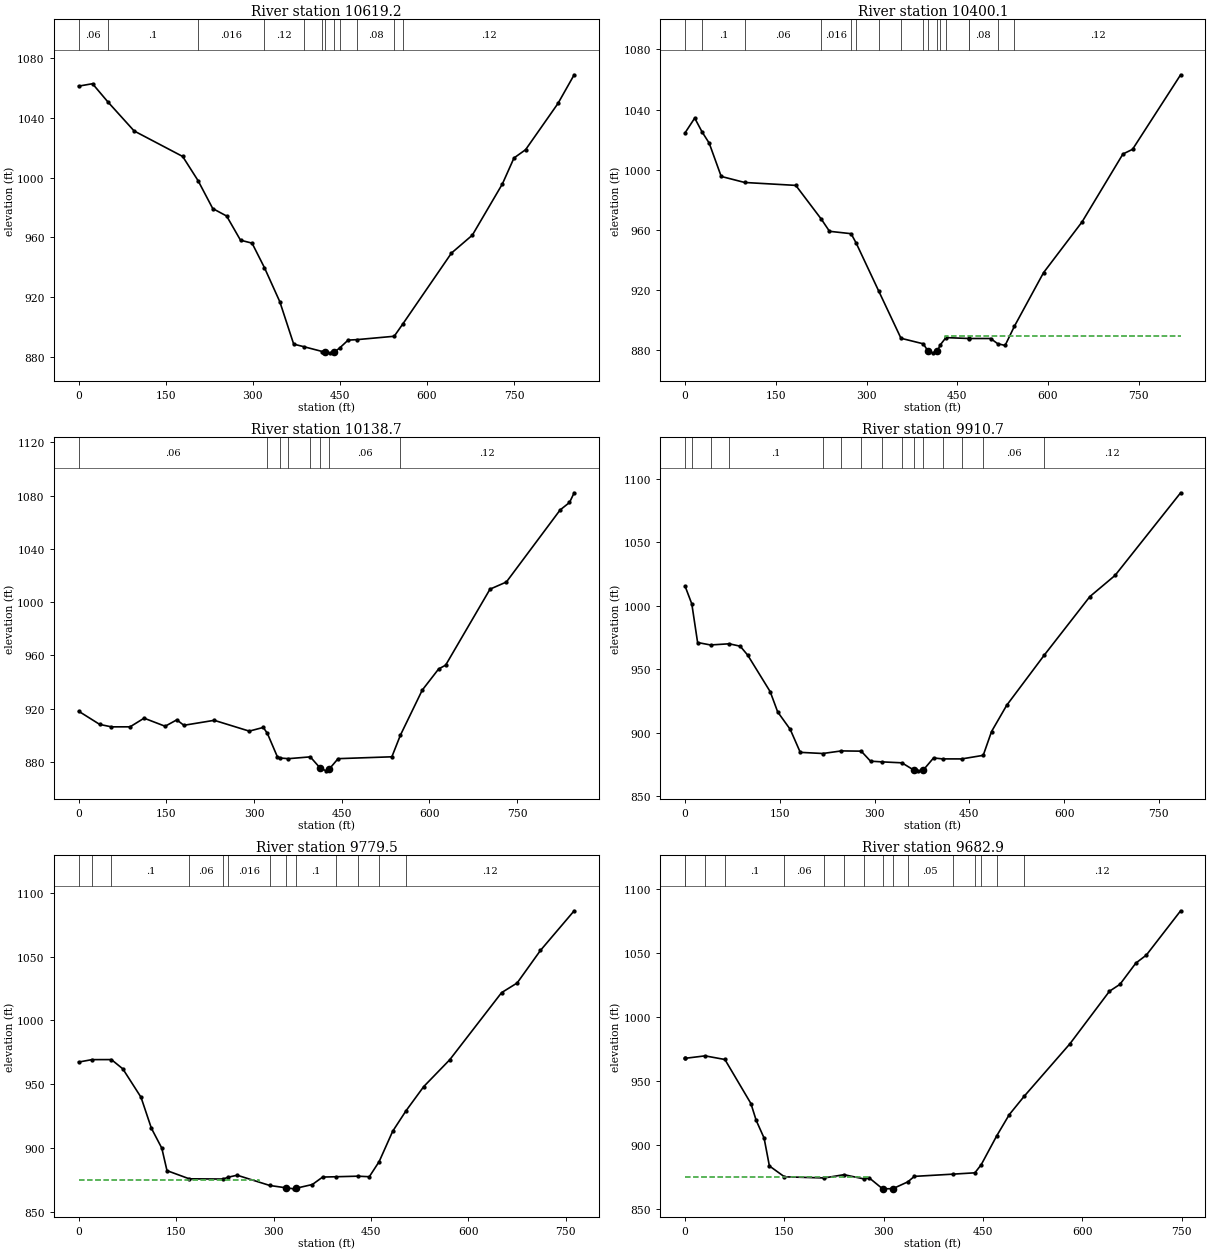
Type RM Length L Ch R = 1 ,10619.2 ,203.5,219.1,239.9
XS GIS Cut Line= 4
     1758449.197      372149.829     1758089.822      371951.913
     1757997.808      371959.725     1757691.385      371788.718
#Sta/Elev= 30
       0 1061.34    23.9 1062.95   50.311050.809    95.6 1031.32   179.2 1014.25
  205.67998.0823     231  979.36   254.9  974.37   278.8  958.18   298.7   956.2
  320.07939.7634   346.5     917   370.4  888.59  387.51886.9078   419.9 883.635
   424.9  883.04   433.4  882.76   439.9  883.11  449.54885.9915   464.1  891.27
  479.18891.5949  543.53893.8576  558.52902.1854   642.2  949.58   678.1  961.55
   729.9  995.88   749.8 1013.22   769.8 1018.77   825.6 1049.74   853.5 1068.94
#Mann= 12 ,-1 , 0
       0     .06       0   50.31      .1       0  205.67    .016       0
  320.07     .12       0  387.51    .016       0   419.9     .06       0
   424.9    .045       0   439.9     .06       0  449.54      .1       0
  479.18     .08       0  543.53     .06       0  558.52     .12       0
Bank Sta=424.9,439.9
XS Rating Curve= 0 ,0
Exp/Cntr=0.3,0.1

Type RM Length L Ch R = 1 ,10400.1 ,262.1,261.5,260
XS GIS Cut Line= 3
     1758543.018      372037.987     1758215.169      371792.268
     1757894.796      371537.276
#Sta/Elev= 30
       0 1024.59    15.9 1034.37   28.211025.059    39.8 1017.75    59.7  995.57
   98.51991.5474     183  989.61  225.19967.1503   238.7  959.08  274.44957.4884
  283.06951.0439  319.98919.4305  356.89887.9368   393.8  884.24   401.9   879.2
   409.7  878.25   416.9  879.29  421.71883.4713  431.19888.3875  468.94887.7835
  469.14887.7871   505.1  887.78  516.57884.3662     529  883.14  544.44 895.969
   592.6  931.59   656.2   965.3   723.8 1010.48   739.7 1013.59   819.2 1063.17
#Mann= 17 ,-1 , 0
       0     .06       0   28.21      .1       0   98.51     .06       0
  225.19    .016       0  274.44     .06       0  283.06      .1       0
  319.98     .12       0  356.89    .016       0   393.8      .1       0
   401.9    .045       0   416.9      .1       0  421.71     .06       0
  431.19     .05       0  468.94     .06       0  469.14     .08       0
  516.57     .06       0  544.44     .12       0
#XS Ineff= 2 , 0
                          430.07          889.16
Permanent Ineff=
       F       F
Bank Sta=401.9,416.9
XS Rating Curve= 0 ,0
Exp/Cntr=0.3,0.1

Type RM Length L Ch R = 1 ,10138.7 ,232.5,228,223.3
XS GIS Cut Line= 2
     1758728.523      371835.208     1758034.513      371348.229
#Sta/Elev= 30
       0  918.08      36  908.17      56  906.32      88  906.34     112  912.84
     148  906.77     168  911.59     180  907.49     232  911.23   291.9  903.11
   315.9  905.89  322.92901.3954   339.9  883.95  344.89882.8854  359.01882.4178
  396.31883.7664   413.8  875.08   423.9  873.27   428.8  874.64   443.9  882.42
   535.9  883.82  550.56 900.126   587.9  933.94   615.9   949.8   627.9  952.68
   703.8 1009.77   731.8 1015.14   823.8  1069.3   839.8 1074.89   847.8 1082.19
#Mann= 8 ,-1 , 0
       0     .06       0  322.92     .04       0  344.89     .06       0
  359.01    .016       0  396.31     .06       0   413.8    .045       0
   428.8     .06       0  550.56     .12       0
Bank Sta=413.8,428.8
XS Rating Curve= 0 ,0
Exp/Cntr=0.3,0.1

Type RM Length L Ch R = 1 ,9910.7  ,155.9,131.2,106.4
XS GIS Cut Line= 3
     1758858.732      371461.076     1758601.787      371442.847
      1758118.28      371233.646
#Sta/Elev= 30
       0 1015.32   10.621001.407    19.8  971.01   40.23969.0768   69.84970.0014
    87.2  968.11    99.1  961.07   134.7  932.31   146.6  916.31   166.4  902.63
   182.3  884.54  217.89883.6277   247.5885.6725   278.8885.4723   293.5  877.59
  310.98 877.058  343.17876.2927   361.7  870.68   369.3  869.98   376.7  870.42
   393.3  880.13  407.53879.3856   437.8879.3665   471.9 882.181   485.1  900.94
     509  921.54  568.44961.0203   640.7 1007.16   680.6 1023.84   784.4 1088.89
#Mann= 15 ,-1 , 0
       0     .08       0   10.62    .016       0   40.23     .06       0
   69.84      .1       0  217.89     .06       0   247.5     .05       0
   278.8     .06       0  310.98    .016       0  343.17     .06       0
   361.7    .045       0   376.7     .05       0  407.53     .06       0
   437.8     .08       0   471.9     .06       0  568.44     .12       0
Bank Sta=361.7,376.7
XS Rating Curve= 0 ,0
Exp/Cntr=0.3,0.1

Type RM Length L Ch R = 1 ,9779.5  ,92.7,96.6,83.5
XS GIS Cut Line= 4
      1758868.28      371290.937     1758612.117      371246.753
     1758504.825      371308.212     1758167.759      371134.687
#Sta/Elev= 30
       0  967.41   20.44969.3321   50.41969.3723      68  962.11      96  939.86
     112  915.54     128  899.98     136  882.34   170.3875.9343  222.39 875.766
  230.24 877.212     244  878.76  294.29870.6985   319.7  868.85   331.7  868.08
   334.7  868.55   359.7  871.46   375.6  877.32   396.1877.5513  429.32878.0007
   447.4  877.58  462.54889.4214   483.4  913.24   503.9 929.252   531.2  948.25
   571.2  969.25     651 1021.84   674.9 1029.38   710.8 1054.92   762.7 1085.98
#Mann= 13 ,-1 , 0
       0    .016       0   20.44     .08       0   50.41      .1       0
   170.3     .06       0  222.39     .08       0  230.24    .016       0
  294.29      .1       0   319.7    .045       0   334.7      .1       0
   396.1     .06       0  429.32     .08       0  462.54     .06       0
   503.9     .12       0
#XS Ineff= 2 , 0
          278.22  875.34
Permanent Ineff=
       F       F
Bank Sta=319.7,334.7
XS Rating Curve= 0 ,0
Exp/Cntr=0.3,0.1

Type RM Length L Ch R = 1 ,9682.9  ,78,92.4,123.6
XS GIS Cut Line= 4
     1758877.829      371229.306     1758599.617      371180.955
     1758492.325      371242.413     1758187.725      371086.076
#Sta/Elev= 30
       0  967.74     .16967.7108   30.14969.6193   60.12966.7811    99.4  932.35
   107.4  919.13   119.3  905.36   127.3  883.56  150.05875.0692  210.01874.1661
  239.99876.7239  269.97873.4302   278.4  874.09   298.3  865.66   298.8  865.67
   313.8  865.79  336.36871.1148   346.2   875.4  404.44 877.142  437.68878.1906
  447.22884.5444  470.87907.3076   489.6  923.69  511.89937.9024   581.2  979.07
   640.9 1020.14   656.8 1025.57   680.7 1042.12   696.6  1048.4   748.4 1083.05
#Mann= 16 ,-1 , 0
       0     .08       0     .16    .016       0   30.14     .06       0
   60.12      .1       0  150.05     .06       0  210.01     .08       0
  239.99    .016       0  269.97     .06       0   298.8    .045       0
   313.8     .06       0  336.36     .05       0  404.44     .08       0
  437.68     .06       0  447.22     .12       0  470.87     .06       0
  511.89     .12       0
#XS Ineff= 2 , 0
          278.09   874.7
Permanent Ineff=
       F       F
Bank Sta=298.8,313.8
XS Rating Curve= 0 ,0
Exp/Cntr=0.3,0.1