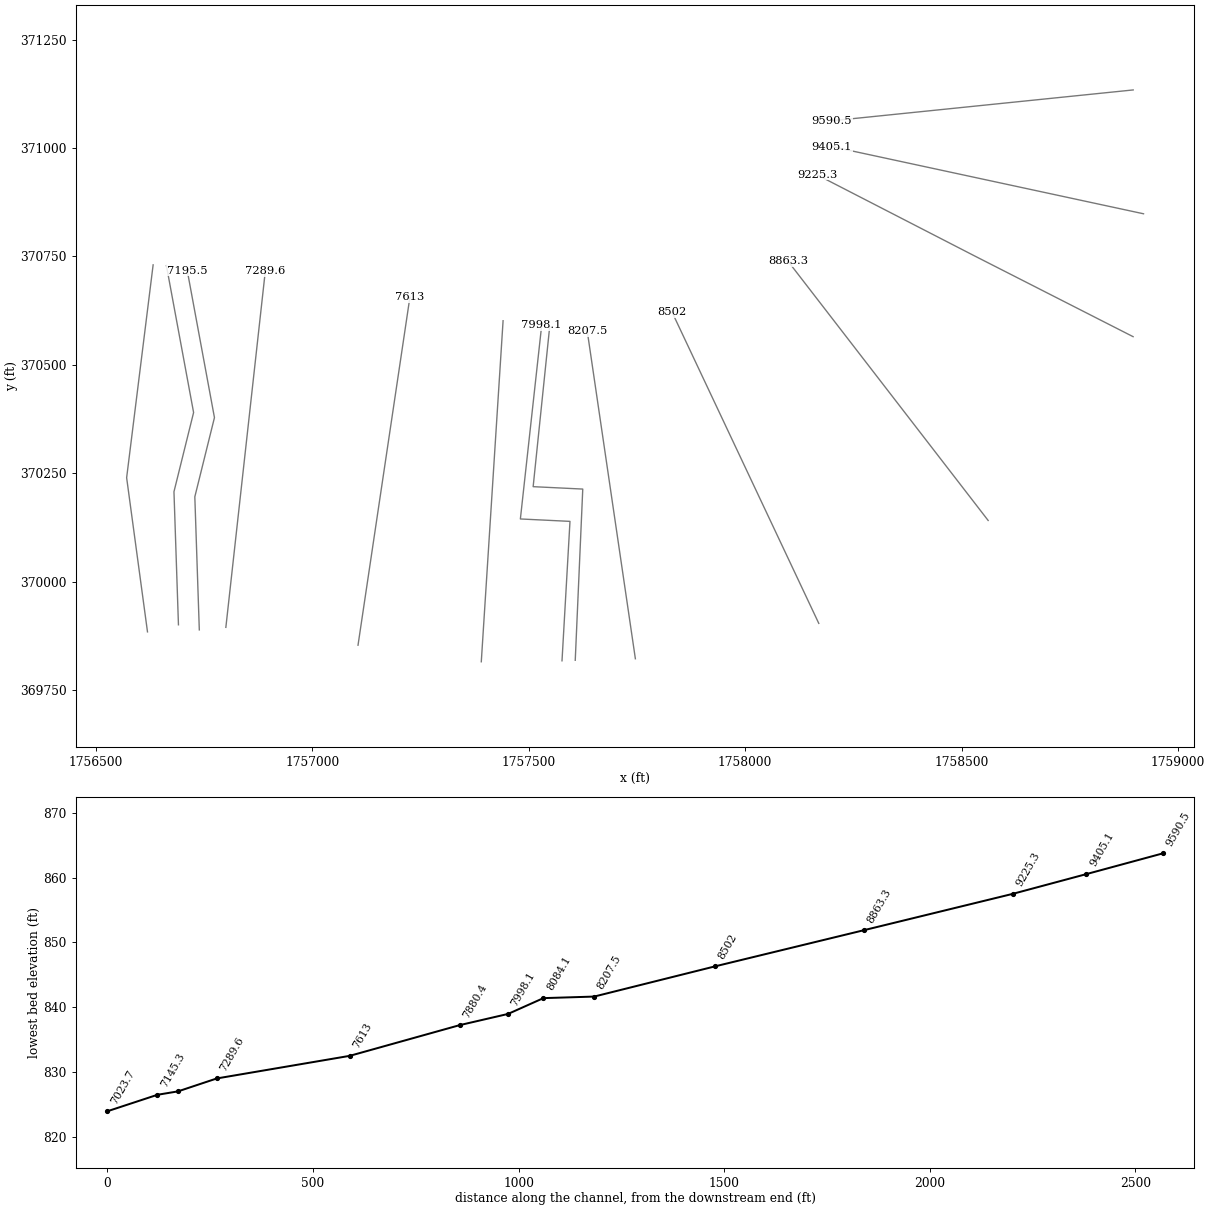
HEC-RAS study ROBINSONCK.prj: ROBINSONCK

--- ROBINSONCK.g01 (geometry) --- (continued)

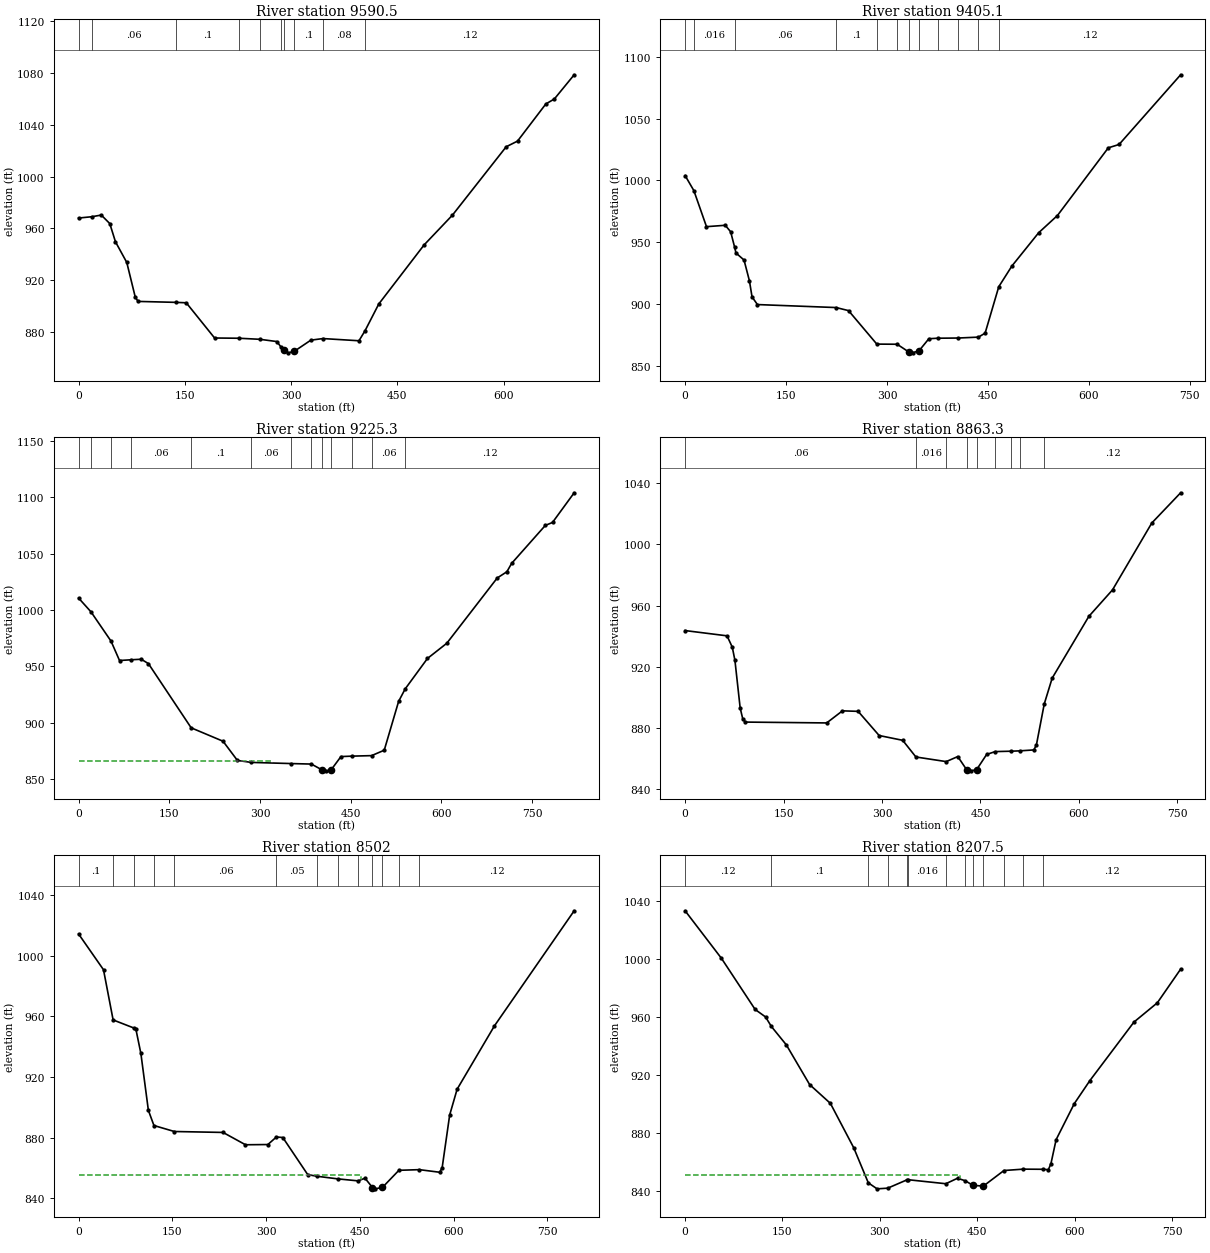
Type RM Length L Ch R = 1 ,9590.5  ,192.4,185.4,178.3
XS GIS Cut Line= 2
     1758896.058      371133.819     1758199.877      371062.639
#Sta/Elev= 30
       0  967.96   18.49968.9623      32  970.26      44  963.67      52  949.62
      68  933.61      80  906.75      84  903.49  137.24902.7623     152  902.43
     192   875.2  226.31875.0181     256 874.195   279.9  872.46  285.69868.2949
   289.7  865.72   295.9  863.73   304.7  864.98   327.9  873.53  345.07  874.77
   395.9  873.07  404.45 880.809   423.9  901.53   487.9  947.19   527.9  970.21
   603.8 1023.07   619.8 1027.44   659.8 1056.18   671.8 1060.01   699.8 1078.73
#Mann= 10 ,-1 , 0
       0    .016       0   18.49     .06       0  137.24      .1       0
  226.31     .06       0     256    .016       0  285.69      .1       0
   289.7    .045       0   304.7      .1       0  345.07     .08       0
  404.45     .12       0
Bank Sta=289.7,304.7
XS Rating Curve= 0 ,0
Exp/Cntr=0.3,0.1

Type RM Length L Ch R = 1 ,9405.1  ,185.6,179.8,173.8
XS GIS Cut Line= 2
      1758919.93      370848.229     1758199.877      371003.177
#Sta/Elev= 30
       0 1003.99   13.03991.7986    31.8  962.63    59.7  963.75    67.7  958.51
   73.45946.3787    75.6  941.34    87.6  935.62    95.6  918.82    99.5  905.82
   107.5   899.6  224.51  897.18   242.9   894.7  284.93867.6082  315.14 867.492
     333  861.05   338.4  860.54     348  862.41   362.3  871.96  375.56872.3692
  405.78872.5264  435.99873.2541   445.9  876.47   466.2 914.053   485.7  930.79
   525.5  957.72   553.4  971.66     629 1026.43     645 1029.13   736.5 1085.53
#Mann= 12 ,-1 , 0
       0     .12       0   13.03    .016       0   73.45     .06       0
  224.51      .1       0  284.93    .016       0  315.14      .1       0
     333    .045       0     348      .1       0  375.56     .06       0
  405.78     .08       0  435.99     .06       0   466.2     .12       0
Bank Sta=333,348
XS Rating Curve= 0 ,0
Exp/Cntr=0.3,0.1

Type RM Length L Ch R = 1 ,9225.3  ,371.9,362,352.2
XS GIS Cut Line= 3
     1758895.863      370564.833     1758530.498      370750.645
     1758166.164      370937.878
#Sta/Elev= 30
       0  1010.6   20.43998.4149   53.57972.4736    67.6  955.28    86.7 955.925
   103.5  956.41   115.4  952.53  186.11 895.611   238.8  883.72   262.6   866.7
  285.51864.9557  351.78 863.926  384.92863.4791   402.4  858.36   409.9  857.48
   417.4  858.24   433.8  870.12  451.28870.4979  484.49870.9642   505.4  875.76
   529.2  919.07  539.99930.0724   576.9  957.11   608.8  970.54   692.3 1028.46
   708.2 1033.94   716.1 1041.38   771.8 1075.03   783.7 1077.67   819.5 1103.96
#Mann= 13 ,-1 , 0
       0     .12       0   20.43     .08       0   53.57    .016       0
    86.7     .06       0  186.11      .1       0  285.51     .06       0
  351.78    .016       0  384.92     .05       0   402.4    .045       0
   417.4      .1       0  451.28     .06       0  484.49     .06       0
  539.99     .12       0
#XS Ineff= 2 , 0
          319.93  866.36
Permanent Ineff=
       F       F
Bank Sta=402.4,417.4
XS Rating Curve= 0 ,0
Exp/Cntr=0.3,0.1

Type RM Length L Ch R = 1 ,8863.3  ,366.2,361.3,356.4
XS GIS Cut Line= 2
      1758561.08      370140.998     1758099.274       370738.22
#Sta/Elev= 30
       0  943.64    63.9   940.2    71.9  932.75    75.9  924.18    83.9  892.99
    87.9  885.76    91.9  883.77   215.7  883.21   239.7  891.12   263.6  890.79
   295.6  874.98   331.5  871.84   351.6860.9355  397.79857.9137   415.4  861.21
   429.1  852.48   435.4  851.87   444.1  852.65   459.4  862.61  472.46864.4579
  496.44 864.717   509.8 864.945   531.3  865.55   535.2  868.85  547.13895.6327
   559.2  912.52   615.1  952.95   651.1  970.25     711 1014.03   754.9 1033.79
#Mann= 9 ,-1 , 0
       0     .06       0   351.6    .016       0  397.79      .1       0
   429.1    .045       0   444.1     .12       0  472.46     .08       0
  496.44     .06       0   509.8     .06       0  547.13     .12       0
Bank Sta=429.1,444.1
XS Rating Curve= 0 ,0
Exp/Cntr=0.3,0.1

Type RM Length L Ch R = 1 ,8502    ,301.1,294.5,287.8
XS GIS Cut Line= 2
     1758169.872      369903.683      1757831.33      370620.697
#Sta/Elev= 30
       0  1014.3    39.8  990.75   55.18957.6781   87.84952.4295    91.6  951.61
    99.6  935.56   111.6  898.05   120.5  888.05  153.17884.1025   231.1  883.49
     267  875.36   302.8  875.51  316.48880.4976   326.7  880.14   366.6  855.66
  381.81854.5759  414.47 852.877  447.13851.5529   458.2  853.32   470.2  847.15
   474.2   846.3   486.1  847.24  512.46858.5183  545.12858.9503   577.8  857.23
   581.7  860.31   593.7  894.99   605.6  911.99   665.4   953.8   792.9 1029.64
#Mann= 13 ,-1 , 0
       0      .1       0   55.18     .05       0   87.84     .06       0
   120.5     .05       0  153.17     .06       0  316.48     .05       0
  381.81    .016       0  414.47     .05       0  447.13     .12       0
   470.2    .045       0   486.1     .12       0  512.46     .08       0
  545.12     .12       0
#XS Ineff= 2 , 0
           451.6  855.74
Permanent Ineff=
       F       F
Bank Sta=470.2,486.1
XS Rating Curve= 0 ,0
Exp/Cntr=0.3,0.1

Type RM Length L Ch R = 1 ,8207.5  ,80.2,123.4,156.8
XS GIS Cut Line= 2
     1757746.261      369822.086     1757635.149      370577.295
#Sta/Elev= 30
       0 1033.21      56 1000.44   107.9  965.21   123.9  960.07  132.92953.4862
   155.9  940.84   191.8  913.48   223.8  900.52   259.8  869.88  282.19845.7692
   295.7  841.63  312.04842.0851   341.9 847.855  343.85847.8937   401.6  845.15
   419.6  848.92  431.46847.2062   443.6  843.97   459.6  843.58  491.17854.2556
  521.02855.2029  550.87   855.1   559.5  854.83   563.5  858.94   571.5  875.52
   599.5  900.34   623.5  916.21   691.4  956.54   727.4   969.8   763.3     993
#Mann= 13 ,-1 , 0
       0     .12       0  132.92      .1       0  282.19     .06       0
  312.04     .05       0   341.9     .06       0  343.85    .016       0
   401.6     .05       0  431.46     .12       0   443.6    .045       0
   459.6     .12       0  491.17     .06       0  521.02     .05       0
  550.87     .12       0
#XS Ineff= 2 , 0
           422.7   851.1
Permanent Ineff=
       F       F
Bank Sta=443.6,459.6
XS Rating Curve= 0 ,0
Exp/Cntr=0.3,0.1

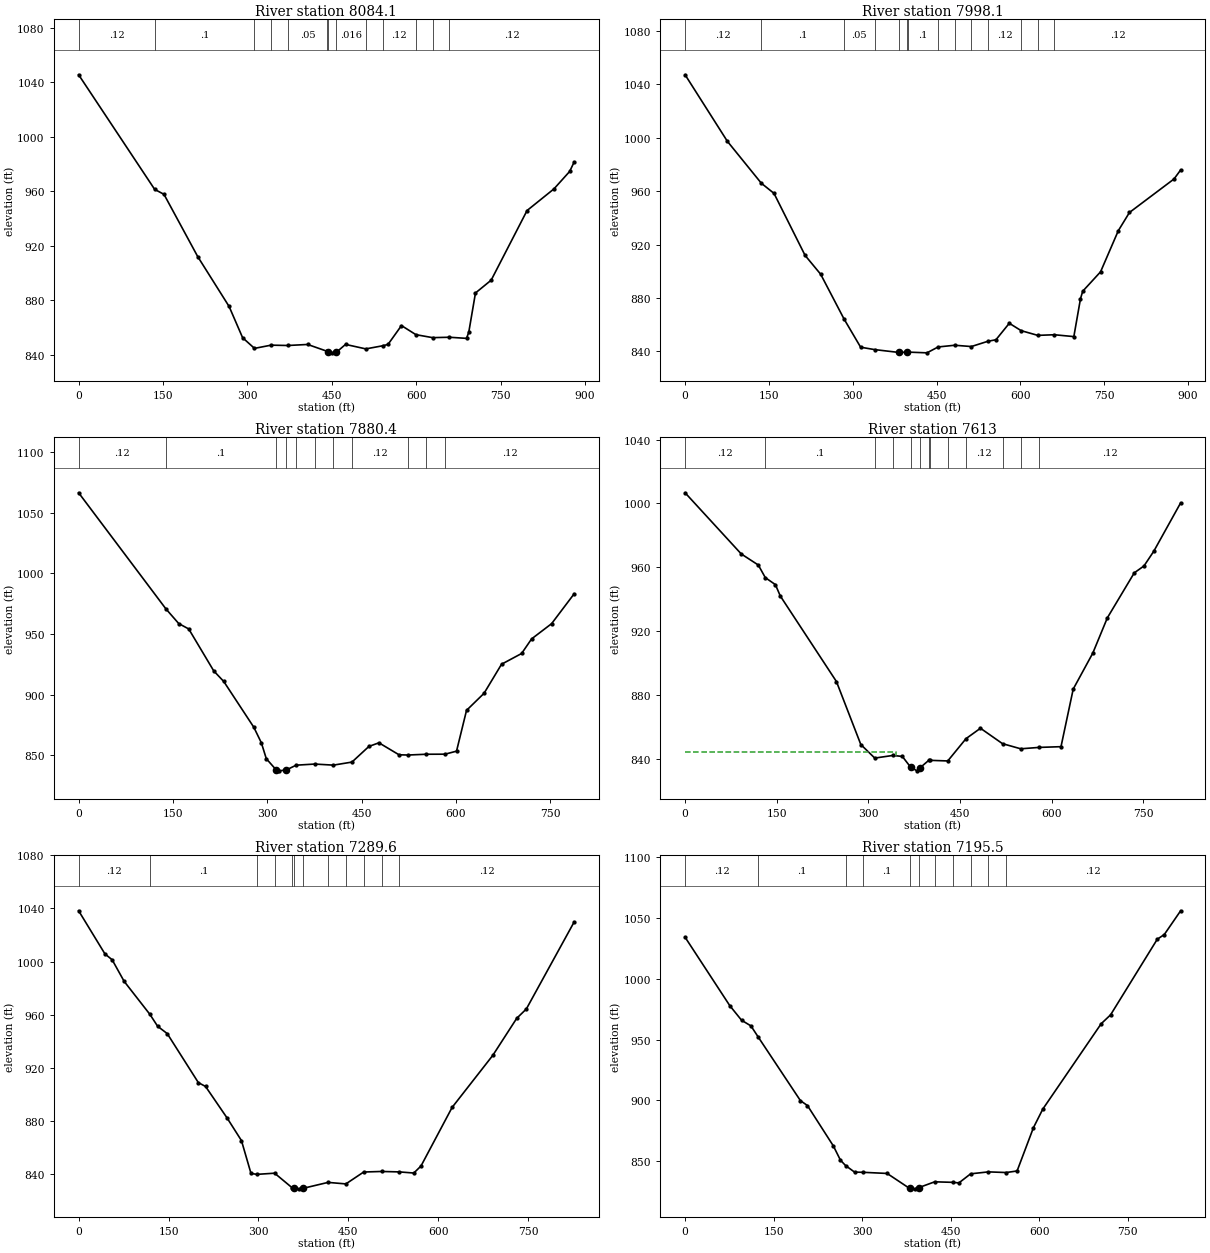
Type RM Length L Ch R = 1 ,8084.1  ,95.8,86,95.3
XS GIS Cut Line= 4
     1757607.372      369818.614     1757624.733      370213.406
     1757510.149      370218.961     1757548.344      370587.711
#Sta/Elev= 30
       0 1045.59  135.11961.4377   151.7  957.78   211.6  912.08   267.4  875.44
   291.4   852.5   312.5844.6656  342.06847.0363  371.62  846.78     407  847.54
  441.89842.4875   442.7  842.32   450.6  841.39   457.7   841.7   474.3  847.58
  510.35844.2876  540.04 846.552   549.8  847.58   573.7  861.41  599.43854.7249
  629.13 852.548  658.82852.8367   689.3  852.02   693.3  856.53   705.2  885.35
   733.1  894.75   796.9   945.9   844.7   961.8   872.6  974.61   880.6  981.55
#Mann= 13 ,-1 , 0
       0     .12       0  135.11      .1       0   312.5     .05       0
  342.06    .016       0  371.62     .05       0  441.89    .016       0
   442.7    .045       0   457.7    .016       0  510.35      .1       0
  540.04     .12       0  599.43     .06       0  629.13     .06       0
  658.82     .12       0
Bank Sta=442.7,457.7
XS Rating Curve= 0 ,0
Exp/Cntr=0.3,0.1

Type RM Length L Ch R = 1 ,7998.1  ,156.4,117.7,69.7
XS GIS Cut Line= 4
     1757576.801      369817.364     1757595.219      370138.926
     1757480.636      370144.482     1757529.926       370591.67
#Sta/Elev= 30
       0 1047.24    75.6  997.43  136.45965.9857   159.1   958.4   214.7  911.94
   242.6  897.82  284.37864.3229   314.1  843.17  339.26841.3654   382.7  839.24
   397.7   839.5   398.4 839.508   432.8  838.95  452.77843.3558  482.48844.6358
   512.2843.6672  541.91847.6226   556.2  848.74   580.1   861.1  601.34855.5609
  631.06852.0354  660.77852.5045   695.6  851.11   707.5  879.52   711.5   885.1
   743.4  899.63   775.2  930.47   795.1  944.08   874.8  969.16   886.7  975.92
#Mann= 14 ,-1 , 0
       0     .12       0  136.45      .1       0  284.37     .05       0
  339.26     .06       0   382.7    .045       0   397.7     .06       0
   398.4      .1       0  452.77     .06       0  482.48    .016       0
   512.2      .1       0  541.91     .12       0  601.34     .06       0
  631.06     .08       0  660.77     .12       0
Bank Sta=382.7,397.7
XS Rating Curve= 0 ,0
Exp/Cntr=0.3,0.1

Type RM Length L Ch R = 1 ,7880.4  ,269.3,267.4,265.5
XS GIS Cut Line= 2
     1757390.358      369815.142     1757440.705        370601.6
#Sta/Elev= 30
       0 1066.57  138.74970.8474   159.2   958.7   175.1  954.25   214.9  919.64
   230.8  910.93   278.6  873.18   290.6  860.35   298.5  847.19   314.4  837.91
   318.4  837.22   330.4  837.96  345.92841.8839  375.51842.8113  405.11841.9257
   434.7844.4465   461.7  857.37   477.6  860.34   509.5  850.47  523.49850.2575
  553.09850.9089  582.68 850.957     601  853.45   616.9  887.09   644.8   901.2
   672.6  925.15   704.5  934.01   720.4  946.05   752.2  958.61   788.1  983.26
#Mann= 11 ,-1 , 0
       0     .12       0  138.74      .1       0   314.4    .045       0
   330.4      .1       0  345.92     .06       0  375.51    .016       0
  405.11      .1       0   434.7     .12       0  523.49     .06       0
  553.09     .06       0  582.68     .12       0
Bank Sta=314.4,330.4
XS Rating Curve= 0 ,0
Exp/Cntr=0.3,0.1

Type RM Length L Ch R = 1 ,7613    ,322.5,323.4,324.3
XS GIS Cut Line= 2
     1757105.636      369853.336     1757225.427       370655.42
#Sta/Elev= 30
       0 1006.68    91.9  968.36   119.8  961.42  131.25953.5315   147.8  949.13
   155.8  942.02   247.7  888.41   287.6  848.95  310.43840.4722  340.29842.1365
   355.6  841.48   368.9  834.87   379.5  832.48   383.9   834.2  398.98839.1173
  400.02 839.077  429.88838.6747  459.74852.6499   483.4  859.16  519.47849.5023
  549.33 846.287  579.19847.1563   615.2  847.62   635.2  883.71   667.2  906.19
   691.1  928.36   735.1  956.51     751  960.84     767  970.02     811 1000.35
#Mann= 13 ,-1 , 0
       0     .12       0  131.25      .1       0  310.43     .05       0
  340.29     .12       0   368.9    .045       0   383.9     .12       0
  398.98     .06       0  400.02    .016       0  429.88      .1       0
  459.74     .12       0  519.47     .08       0  549.33     .06       0
  579.19     .12       0
#XS Ineff= 2 , 0
          345.72  843.99
Permanent Ineff=
       F       F
Bank Sta=368.9,383.9
XS Rating Curve= 0 ,0
Exp/Cntr=0.3,0.1

Type RM Length L Ch R = 1 ,7289.6  ,97.1,94.1,91.1
XS GIS Cut Line= 2
     1756800.388       369894.51     1756891.534      370716.125
#Sta/Elev= 30
       0 1038.19    43.9 1005.73    55.9 1001.34    75.9  985.11   118.9960.2415
   131.8   951.3   147.8  945.78   199.7  908.91   211.7  906.02   247.6  882.33
   271.6  865.29   287.5  840.62   297.2839.8818  326.92840.7595  356.64 829.608
   358.5  829.32   367.4  828.99   373.5  829.28  416.07833.8354  445.79832.6966
   475.5 841.645  505.22842.0596  534.94841.7332   559.1  840.88   571.1  846.18
     623  890.26   690.9  929.44   730.8   957.3   746.8   964.3   826.6  1029.8
#Mann= 12 ,-1 , 0
       0     .12       0   118.9      .1       0   297.2     .05       0
  326.92      .1       0  356.64     .12       0   358.5    .045       0
   373.5     .12       0  416.07    .016       0  445.79     .12       0
   475.5     .08       0  505.22     .06       0  534.94     .12       0
Bank Sta=358.5,373.5
XS Rating Curve= 0 ,0
Exp/Cntr=0.3,0.1

Type RM Length L Ch R = 1 ,7195.5  ,50.2,50.2,50.2
XS GIS Cut Line= 4
     1756739.082      369888.705     1756728.714      370195.554
     1756774.056      370378.226     1756711.304       370716.83
#Sta/Elev= 30
       0 1034.27    75.8  977.86    95.7   965.9   111.6  961.22  124.06951.9474
   195.4  899.67   207.3  895.62   251.2  862.34   263.2  850.64  271.82 846.219
   287.1  840.79  301.37840.6222   342.3  839.68   380.6  827.28   389.4     827
   395.6  827.94  422.93832.7944  453.36832.3548   463.9  831.89   483.8839.3731
  513.98840.9739  544.02840.4332   562.5  841.72   590.2  877.39   606.1  892.73
     705  963.04   720.9  970.35     800 1032.64   811.9 1036.52   839.6 1056.09
#Mann= 11 ,-1 , 0
       0     .12       0  124.06      .1       0  271.82     .05       0
  301.37      .1       0   380.6    .045       0   395.6     .12       0
  422.93    .016       0  453.36      .1       0   483.8     .08       0
  513.98     .06       0  544.02     .12       0
Bank Sta=380.6,395.6
XS Rating Curve= 0 ,0
Exp/Cntr=0.3,0.1

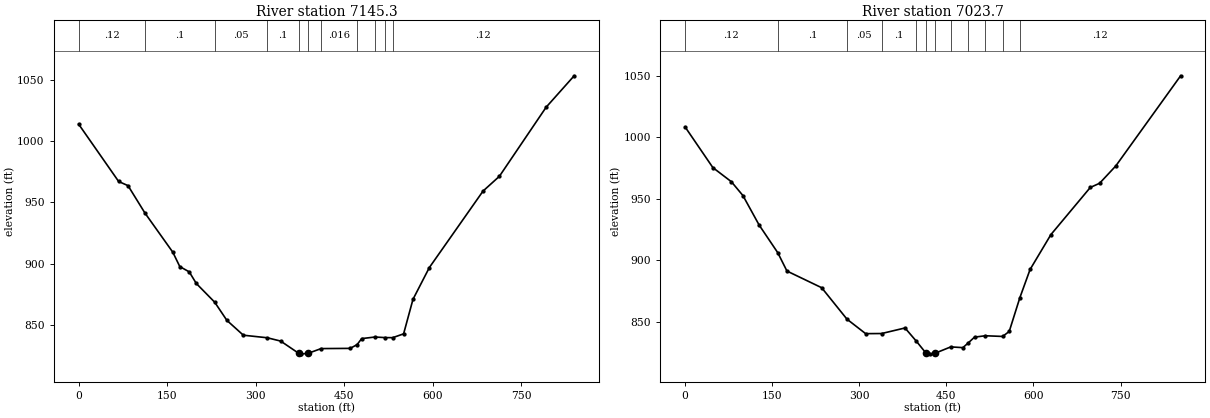
Type RM Length L Ch R = 1 ,7145.3  ,118.9,121.6,124.3
XS GIS Cut Line= 4
     1756690.905      369900.424     1756680.537      370207.272
     1756725.878      370389.945     1756663.127      370728.549
#Sta/Elev= 30
       0 1013.66    67.8  966.94    83.7  963.53  112.33 941.229   159.5  909.35
   171.4  897.59   187.4  893.28   199.4   883.8  230.54868.5489   251.2  853.74
   279.1  841.65  319.56839.5747   342.3  836.87   373.1  826.83   377.6  826.47
   388.1  826.77  410.86830.7466     460  830.92  471.72833.9505   479.6  838.89
  502.07 840.175  519.06839.7103   532.1839.6485   550.6  842.76   566.5   870.9
   594.2  896.78   685.2  959.12   712.9  971.16   792.1 1027.46   839.6 1053.08
#Mann= 11 ,-1 , 0
       0     .12       0  112.33      .1       0  230.54     .05       0
  319.56      .1       0   373.1    .045       0   388.1     .12       0
  410.86    .016       0  471.72      .1       0  502.07     .06       0
  519.06     .05       0   532.1     .12       0
Bank Sta=373.1,388.1
XS Rating Curve= 0 ,0
Exp/Cntr=0.3,0.1

Type RM Length L Ch R = 1 ,7023.7  ,370.1,370.6,370.8
XS GIS Cut Line= 3
     1756619.399      369884.094     1756571.222      370239.562
     1756632.419      370730.448
#Sta/Elev= 30
       0 1008.55    47.8  975.47    79.7  963.97    99.6   952.7   127.5  928.73
  159.58906.2211   175.4   891.3   235.2  877.73  278.81852.1246   310.9  840.36
  338.42840.4534   378.7  844.98  397.98834.3542   414.7  824.61   422.6  823.93
   429.7  824.26   457.5829.5746   478.4  828.98  487.27832.6541   498.4  837.52
  517.03838.6403   546.8  838.09   558.2  842.15  576.56869.6774   594.1  892.56
     630  920.96   697.8  959.29   713.8   962.7   741.7   976.8   853.4 1050.17
#Mann= 12 ,-1 , 0
       0     .12       0  159.58      .1       0  278.81     .05       0
  338.42      .1       0  397.98     .12       0   414.7    .045       0
   429.7     .12       0   457.5    .016       0  487.27     .12       0
  517.03     .06       0   546.8      .1       0  576.56     .12       0
Bank Sta=414.7,429.7
XS Rating Curve= 0 ,0
Exp/Cntr=0.3,0.1