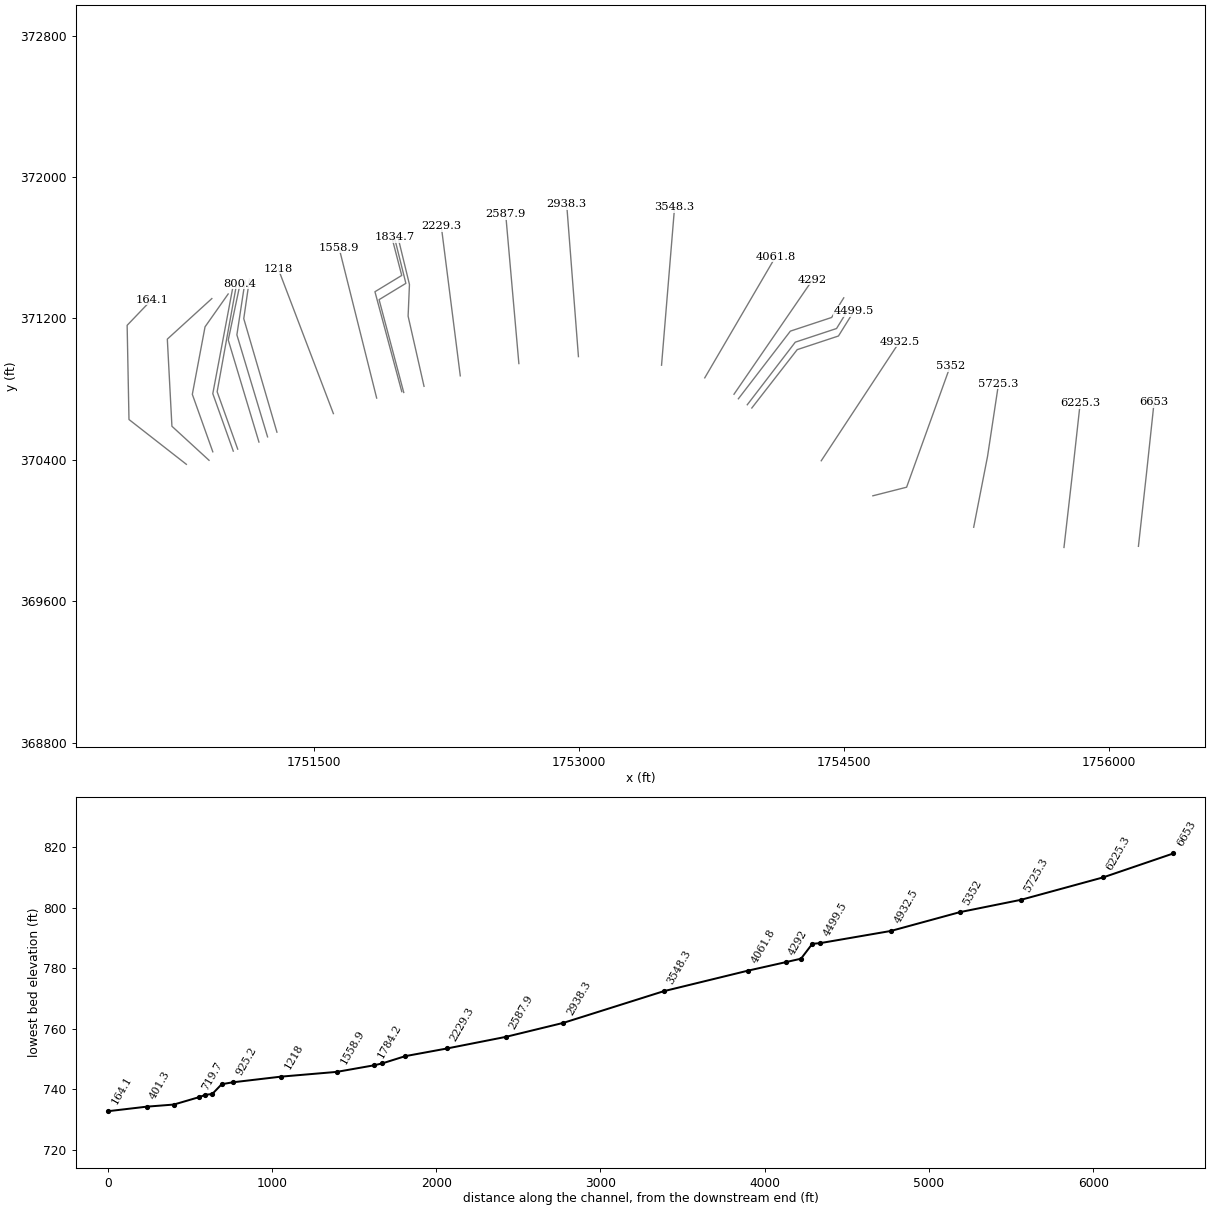
HEC-RAS study ROBINSONCK.prj: ROBINSONCK

--- ROBINSONCK.g01 (geometry) --- (continued)

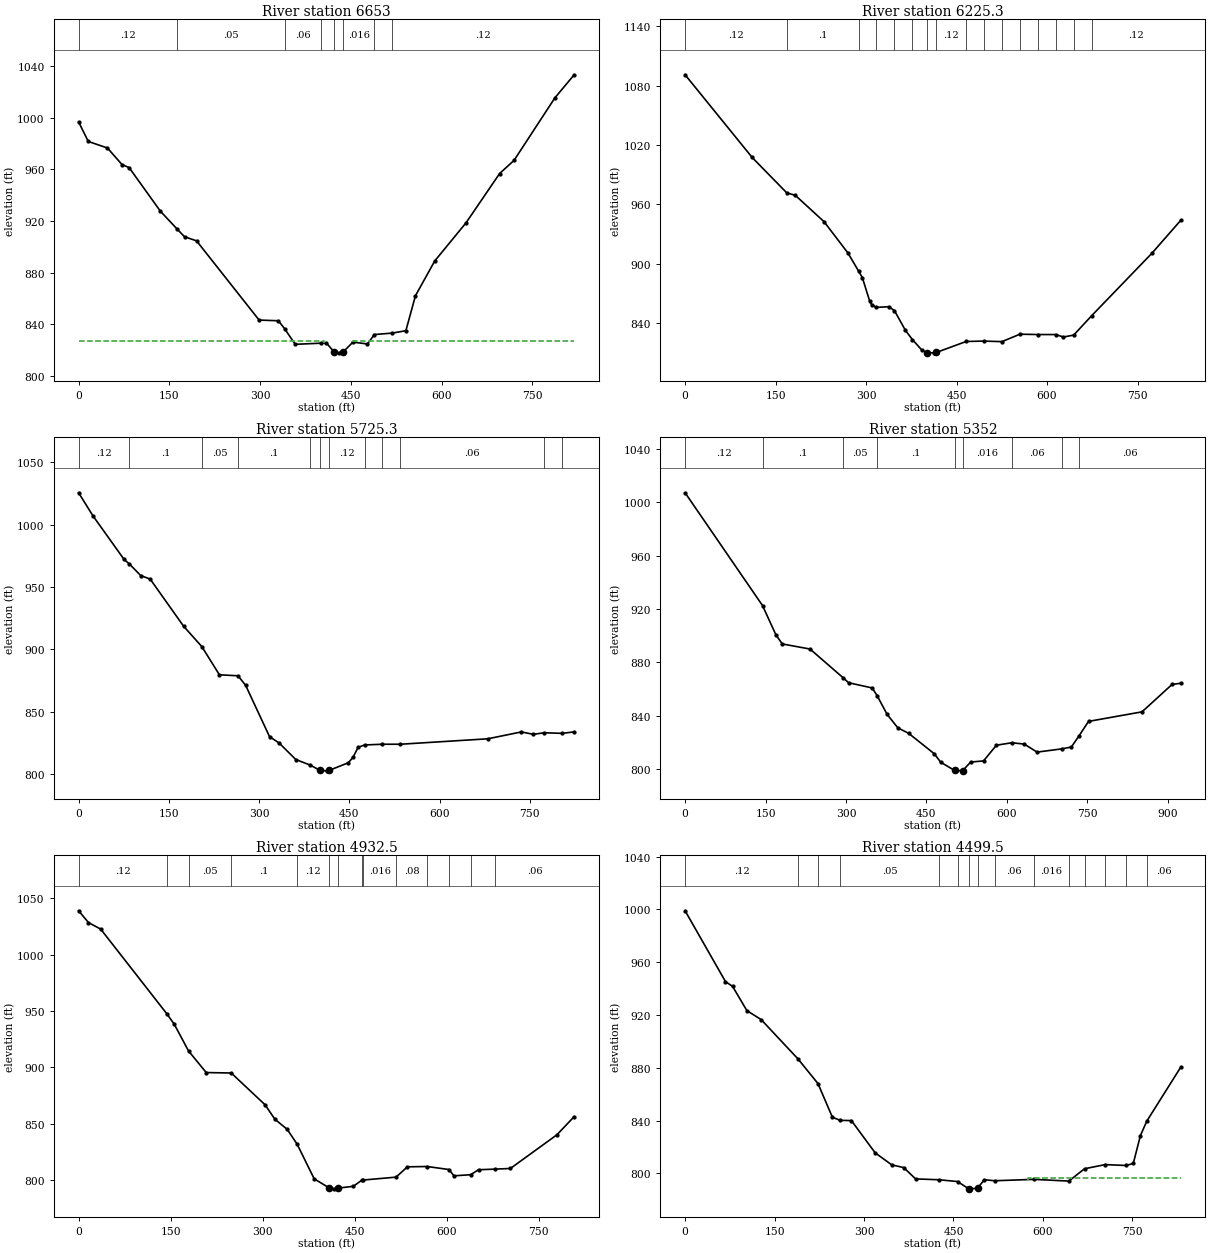
Type RM Length L Ch R = 1 ,6653    ,427.8,427.7,427.6
XS GIS Cut Line= 3
     1756164.783      369910.653     1756209.832      370317.879
     1756253.287      370724.973
#Sta/Elev= 30
       0  996.76    15.9  981.66    47.7  976.58    71.6   963.8    83.5  961.39
   135.2  927.62  162.11914.1509     175  907.86   194.9   904.7   298.3  843.34
   330.2   842.8   340.4836.6973     358  824.56  399.84825.4202   409.7  825.52
   422.6   818.5   429.6  817.96   437.6  818.82   453.4  826.25   477.3  824.84
  488.95832.1132  518.65833.2646   540.9  835.09   556.8  862.23   588.6  889.09
   640.2  918.56   695.9  956.82   719.8  967.06   787.3 1015.45   819.1 1033.29
#Mann= 8 ,-1 , 0
       0     .12       0  162.11     .05       0   340.4     .06       0
  399.84     .12       0   422.6    .045       0   437.6    .016       0
  488.95     .06       0  518.65     .12       0
#XS Ineff= 2 , 0
          405.55  826.87  453.22          827.01
Permanent Ineff=
       F       F
Bank Sta=422.6,437.6
XS Rating Curve= 0 ,0
Exp/Cntr=0.3,0.1

Type RM Length L Ch R = 1 ,6225.3  ,501.6,500,499.2
XS GIS Cut Line= 3
     1755743.407      369904.232     1755789.842      370310.552
     1755835.052      370720.603
#Sta/Elev= 30
       0 1090.99   111.2 1007.44  168.65971.6222   182.6  969.24   230.3   942.6
     270   910.9  287.56892.6467   293.8  886.14   305.7  862.87   309.7   858.3
  317.29855.9565   337.5  856.64  347.02852.7551   365.3  832.71  376.75823.4958
   393.1  812.42   401.5  810.13   412.9  810.04   416.5  810.43   465.9821.5105
  495.62821.9158  525.33821.3599  555.05 828.875  584.76828.5361  614.48828.4976
   627.1  826.04  644.19827.9576  673.91847.5067   773.9  910.67   821.5  943.81
#Mann= 16 ,-1 , 0
       0     .12       0  168.65      .1       0  287.56     .06       0
  317.29     .05       0  347.02      .1       0  376.75     .12       0
   401.5    .045       0   416.5     .12       0   465.9     .08       0
  495.62    .016       0  525.33      .1       0  555.05     .06       0
  584.76    .016       0  614.48      .1       0  644.19     .04       0
  673.91     .12       0
Bank Sta=401.5,416.5
XS Rating Curve= 0 ,0
Exp/Cntr=0.3,0.1

Type RM Length L Ch R = 1 ,5725.3  ,376.7,373.3,368.8
XS GIS Cut Line= 3
      1755232.36       370018.52     1755310.797      370419.428
     1755372.893       370829.87
#Sta/Elev= 30
       0 1025.57    23.8 1007.08    75.4  972.22   84.39968.4669   103.1  959.24
     119  956.32   174.5  918.55  204.78902.2245     234  879.62  264.97878.8479
   277.6  871.14   317.3  830.03   333.2  824.96   360.9  811.71  385.35807.1409
     401  803.03   412.5  802.63     416  802.93   448.4  809.13   456.4  813.75
   464.4  821.43  475.14823.3616  505.01823.9625  534.88823.9644   679.9  828.31
   735.8  833.82   755.8   831.9  773.85833.1683  803.73832.6818   823.6  833.87
#Mann= 12 ,-1 , 0
       0     .12       0   84.39      .1       0  204.78     .05       0
  264.97      .1       0  385.35     .12       0     401    .045       0
     416     .12       0  475.14    .016       0  505.01     .08       0
  534.88     .06       0  773.85     .08       0  803.73     .06       0
Bank Sta=401,416
XS Rating Curve= 0 ,0
Exp/Cntr=0.3,0.1

Type RM Length L Ch R = 1 ,5352    ,424.2,419.5,413.9
XS GIS Cut Line= 3
     1754661.774      370196.554     1754852.746      370245.165
     1755099.274      370929.193
#Sta/Elev= 30
       0 1007.05   144.4922.4736   169.5  900.41   181.3  893.69     233  889.88
  295.36868.1083   304.9  864.61   348.9   860.7  358.15854.9088   376.8  840.87
   396.8  830.76   416.8  826.71   464.7  811.37   476.7     805   502.7  798.82
   516.7  798.54   517.7   798.7   532.6  805.13   556.6  805.98   580.6  817.75
  609.31819.6029   632.5   818.6   656.5  812.58  703.49815.0712   720.4  816.41
  734.89824.8934   752.4  835.62   852.2  842.78   908.2  863.34   924.2   864.2
#Mann= 9 ,-1 , 0
       0     .12       0   144.4      .1       0  295.36     .05       0
  358.15      .1       0   502.7    .045       0   517.7    .016       0
  609.31     .06       0  703.49    .016       0  734.89     .06       0
Bank Sta=502.7,517.7
XS Rating Curve= 0 ,0
Exp/Cntr=0.3,0.1

Type RM Length L Ch R = 1 ,4932.5  ,448.5,433.1,417.9
XS GIS Cut Line= 2
     1754369.616      370394.836     1754813.626      371069.315
#Sta/Elev= 30
       0 1038.88      16 1028.45      36  1022.6   143.7947.5635   155.9  938.22
  179.07 914.618   207.9  895.44   248.7 895.036   303.8  866.87   319.8  854.05
   339.8  845.14  356.14831.8713   383.8  801.23   407.4  793.47   415.8  792.33
   422.4  792.91   447.7  794.61  461.95800.1869  463.57800.1342  517.29802.7042
   535.7  811.85  568.03812.1268  603.39809.4555   611.6  803.86  638.75804.8696
   651.6  809.26  678.44809.8206   703.6  810.38   779.5   840.3   807.5  856.38
#Mann= 14 ,-1 , 0
       0     .12       0   143.7     .06       0  179.07     .05       0
   248.7      .1       0  356.14     .12       0   407.4    .045       0
   422.4      .1       0  461.95     .06       0  463.57    .016       0
  517.29     .08       0  568.03    .016       0  603.39     .06       0
  638.75    .016       0  678.44     .06       0
Bank Sta=407.4,422.4
XS Rating Curve= 0 ,0
Exp/Cntr=0.3,0.1

Type RM Length L Ch R = 1 ,4499.5  ,45,45.1,45.2
XS GIS Cut Line= 4
     1753976.729      370693.391     1754233.548      371023.633
     1754467.055       371100.89     1754555.071      371242.436
#Sta/Elev= 30
       0  998.94    67.7  945.31    79.7  941.63   103.6  923.31   127.5  916.52
  189.19886.7775  222.85868.0331     247  842.51  260.26 840.163   278.9     840
   318.7  815.56   346.6  806.44   366.6  804.38   386.5  795.82  425.73795.1557
  456.84793.8063   475.4  788.38   477.8  788.28   490.4  788.74   501.7  795.18
  519.06794.4132  585.21795.4512   643.5794.1525  669.83803.4985  704.61806.6501
  739.39805.9702   751.6  807.54   763.5  828.56  774.17839.5121     831  880.34
#Mann= 15 ,-1 , 0
       0     .12       0  189.19     .06       0  222.85      .1       0
  260.26     .05       0  425.73      .1       0  456.84     .05       0
   475.4    .045       0   490.4      .1       0  519.06     .06       0
  585.21    .016       0   643.5     .12       0  669.83     .08       0
  704.61    .016       0  739.39     .08       0  774.17     .06       0
#XS Ineff= 2 , 0
                          574.39          796.61
Permanent Ineff=
       F       F
Bank Sta=475.4,490.4
XS Rating Curve= 0 ,0
Exp/Cntr=0.3,0.1

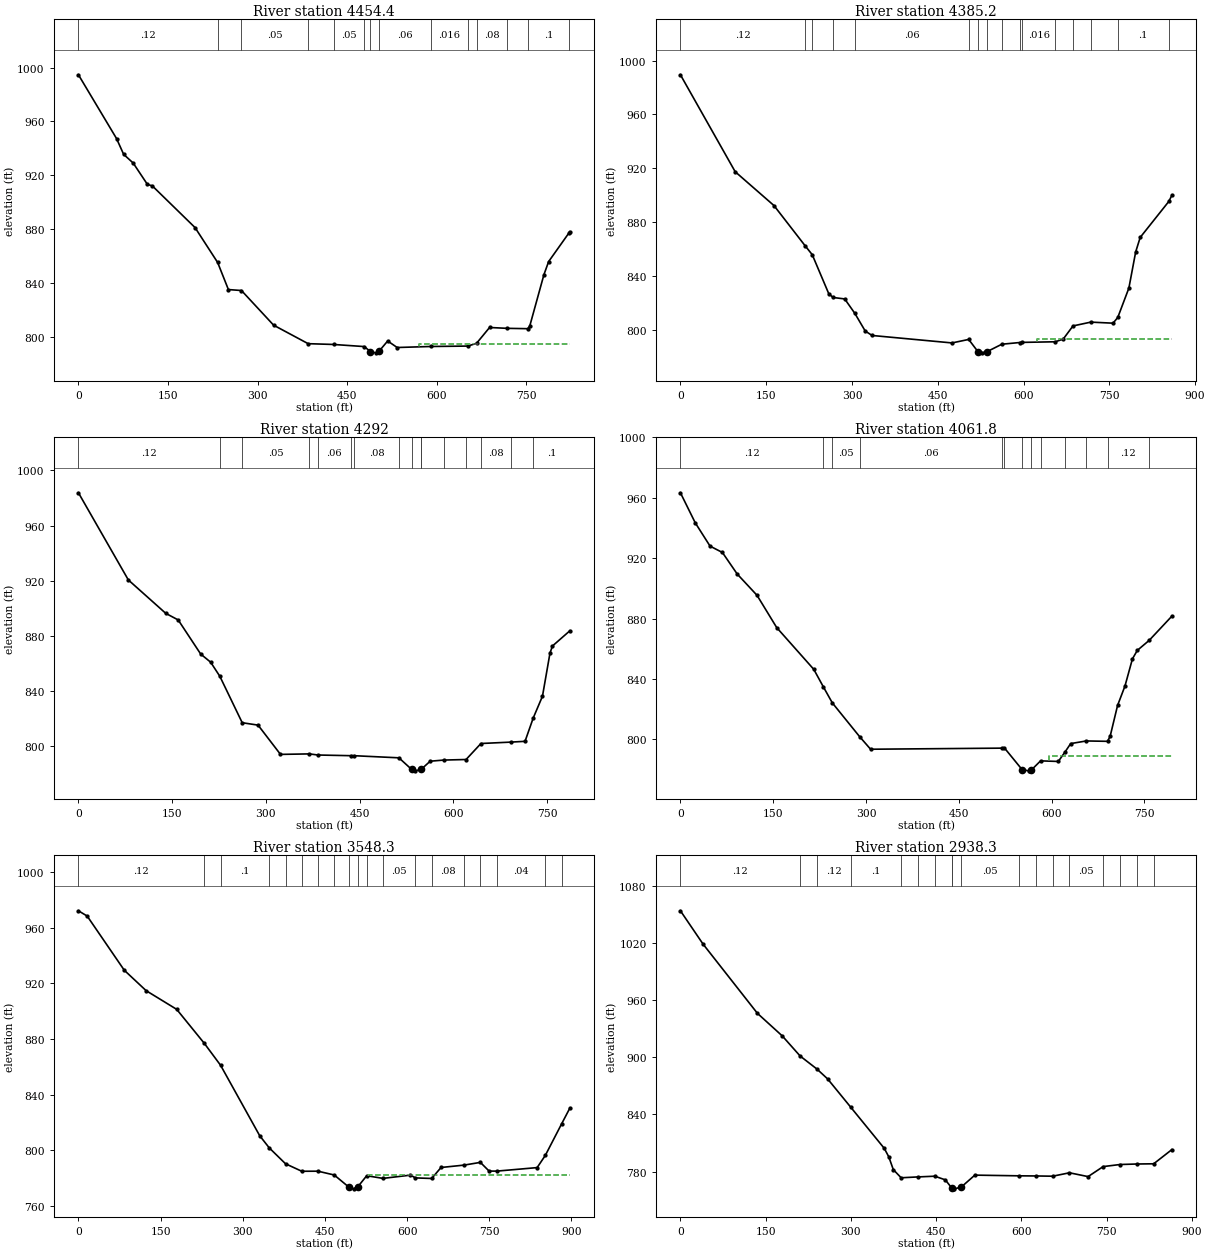
Type RM Length L Ch R = 1 ,4454.4  ,69.2,69.1,69.2
XS GIS Cut Line= 4
     1753950.996      370711.785     1754222.697      371065.951
     1754456.204      371143.208     1754524.781      371254.319
#Sta/Elev= 30
       0  994.69    63.8  947.32    75.7  935.59    91.7   929.1   115.6  913.17
   123.6  912.19   195.3  881.14  233.09855.2469   251.1   835.1  272.99834.3907
   326.8  808.65  384.66794.8931   427.2 794.312  478.53792.7469   488.9  789.05
     498  788.09   503.9  789.58   517.8  796.89   533.7  792.05  589.64 792.809
  651.86793.1163  666.58795.1523   688.4  806.93  717.53   806.3  752.24806.0349
   755.6  807.87   779.4  846.14   787.3   855.9  821.66877.3905   822.9  878.09
#Mann= 14 ,-1 , 0
       0     .12       0  233.09      .1       0  272.99     .05       0
  384.66     .06       0   427.2     .05       0  478.53     .08       0
   488.9    .045       0   503.9     .06       0  589.64    .016       0
  651.86     .12       0  666.58     .08       0  717.53    .016       0
  752.24      .1       0  821.66     .12       0
#XS Ineff= 2 , 0
                          570.51          794.89
Permanent Ineff=
       F       F
Bank Sta=488.9,503.9
XS Rating Curve= 0 ,0
Exp/Cntr=0.3,0.1

Type RM Length L Ch R = 1 ,4385.2  ,78.4,93.2,108
XS GIS Cut Line= 4
     1753900.649      370745.639     1754194.919      371128.451
     1754428.426      371205.708     1754497.003      371316.819
#Sta/Elev= 30
       0  989.42    95.8   917.5   163.6  892.41  218.48862.3494  230.49855.9867
   259.4  827.03  266.95 824.228   287.3  823.14     305 812.447   323.2  799.31
   335.2  796.04   474.9  790.51  504.09793.0999   520.3  784.02   526.5  783.16
   535.3  783.84  562.03789.5518  593.14790.8041  598.11790.9178  655.36 791.368
   669.3  793.33  686.47 803.112  717.58805.9471   756.5  805.16  764.76809.3824
   784.2   831.2   796.1  858.05     804  868.78   854.1895.4999   859.4  900.07
#Mann= 16 ,-1 , 0
       0     .12       0  218.48     .06       0  230.49      .1       0
  266.95     .05       0     305     .06       0  504.09     .08       0
   520.3    .045       0   535.3      .1       0  562.03     .06       0
  593.14      .1       0  598.11    .016       0  655.36     .12       0
  686.47     .08       0  717.58    .016       0  764.76      .1       0
   854.1     .08       0
#XS Ineff= 2 , 0
                          624.35           793.5
Permanent Ineff=
       F       F
Bank Sta=520.3,535.3
XS Rating Curve= 0 ,0
Exp/Cntr=0.3,0.1

Type RM Length L Ch R = 1 ,4292    ,228.6,230.2,231.8
XS GIS Cut Line= 2
     1753875.846      370771.357     1754321.159      371419.795
#Sta/Elev= 30
       0  983.81    79.9  920.54   139.8   896.3   159.7  891.51   195.7  866.76
   211.6  860.87  226.32 850.626  262.14816.9318   287.5  815.18   323.4  793.95
  369.63794.3039  383.38793.4942  435.55793.0074  441.29792.9957  512.95 791.455
   533.2  783.09   539.1  782.01   548.2  783.06  548.78783.1843     563     789
  584.61789.8243  620.44790.2373  644.26801.8458  692.09802.8613   714.8  803.43
  727.92820.3669   742.7  836.16   754.7   867.4   758.7  872.62   786.6  883.67
#Mann= 16 ,-1 , 0
       0     .12       0  226.32      .1       0  262.14     .05       0
  369.63     .08       0  383.38     .06       0  435.55     .05       0
  441.29     .08       0  512.95      .1       0   533.2    .045       0
   548.2     .12       0  548.78     .06       0  584.61    .016       0
  620.44     .06       0  644.26     .08       0  692.09    .016       0
  727.92      .1       0
Bank Sta=533.2,548.2
XS Rating Curve= 0 ,0
Exp/Cntr=0.3,0.1

Type RM Length L Ch R = 1 ,4061.8  ,503.3,513.5,523.5
XS GIS Cut Line= 2
     1753710.385      370864.089     1754111.427      371549.852
#Sta/Elev= 30
       0  963.22      24  943.33    47.9  927.92    67.9   923.7    91.8  909.45
   123.8  895.38   155.7  873.97   215.6  846.35  231.12  834.71  245.56824.1613
  289.63  801.84   307.4   793.5  519.28794.2217  523.67 794.371   552.3  780.01
   562.9   779.2   567.3  779.78  582.18785.8048   610.8  785.41  621.93791.8222
   630.8  797.23  656.14798.9812  690.36798.7298   694.6  802.06   706.6  822.46
   718.6  835.37   730.6  853.27   738.5  858.91  757.71865.5406   794.4  881.57
#Mann= 13 ,-1 , 0
       0     .12       0  231.12     .06       0  245.56     .05       0
  289.63     .06       0  519.28     .05       0  523.67     .06       0
   552.3    .045       0   567.3     .06       0  582.18    .016       0
  621.93     .08       0  656.14    .016       0  690.36     .12       0
  757.71      .1       0
#XS Ineff= 2 , 0
                          595.25          788.85
Permanent Ineff=
       F       F
Bank Sta=552.3,567.3
XS Rating Curve= 0 ,0
Exp/Cntr=0.3,0.1

Type RM Length L Ch R = 1 ,3548.3  ,606,610,613.7
XS GIS Cut Line= 2
     1753465.755      370935.587      1753539.54      371829.684
#Sta/Elev= 30
       0  972.21      16   968.4    83.7  929.48   123.6   914.8   179.4  901.37
  229.87876.9063  259.51861.1693   330.9  810.56  348.42  801.79  378.05790.4138
  407.69785.0331  437.32785.0772  466.96782.3469   494.4  773.39   502.4   772.4
   510.4  774.08  526.23781.8267  555.87779.9132   606.1  782.24  615.14780.2646
  644.78779.8477   661.9  787.74  704.05789.4556  733.68791.4104   749.6  785.17
  763.32785.1259   837.3  787.66  852.23796.4189  881.86818.9926   897.1  830.47
#Mann= 19 ,-1 , 0
       0     .12       0  229.87     .06       0  259.51      .1       0
  348.42     .05       0  378.05     .06       0  407.69     .05       0
  437.32     .12       0  466.96      .1       0   494.4    .045       0
   510.4     .05       0  526.23     .06       0  555.87     .05       0
  615.14    .016       0  644.78     .08       0  704.05    .016       0
  733.68     .06       0  763.32     .04       0  852.23     .12       0
  881.86      .1       0
#XS Ineff= 2 , 0
                          529.42          782.52
Permanent Ineff=
       F       F
Bank Sta=494.4,510.4
XS Rating Curve= 0 ,0
Exp/Cntr=0.3,0.1

Type RM Length L Ch R = 1 ,2938.3  ,349.9,350.4,350.7
XS GIS Cut Line= 2
     1752995.412      370984.208     1752928.831      371846.399
#Sta/Elev= 30
       0 1053.56    39.8 1018.66   135.5  946.01   179.3  922.27  210.65901.2499
  240.27887.5656     259  877.27  299.52847.6976   358.7   804.4   366.6  795.59
   374.6  782.12  388.39773.5544  418.01774.4529  447.64775.1993   466.2  771.35
  477.26762.9374   478.2  762.48   482.2  761.95   494.2  763.84   518.1  776.33
  595.76775.6012  625.38775.4626     655775.1977  684.63778.7861   717.3  774.78
  743.87785.2808   773.5 787.462  803.12787.9895  832.75788.2168   864.8  803.11
#Mann= 18 ,-1 , 0
       0     .12       0  210.65     .06       0  240.27     .12       0
  299.52      .1       0  388.39     .06       0  418.01     .12       0
  447.64     .06       0  477.26     .05       0   478.2    .045       0
   494.2     .05       0  595.76     .08       0  625.38    .016       0
     655     .08       0  684.63     .05       0  743.87     .06       0
   773.5    .016       0  803.12     .12       0  832.75      .1       0
Bank Sta=478.2,494.2
XS Rating Curve= 0 ,0
Exp/Cntr=0.3,0.1

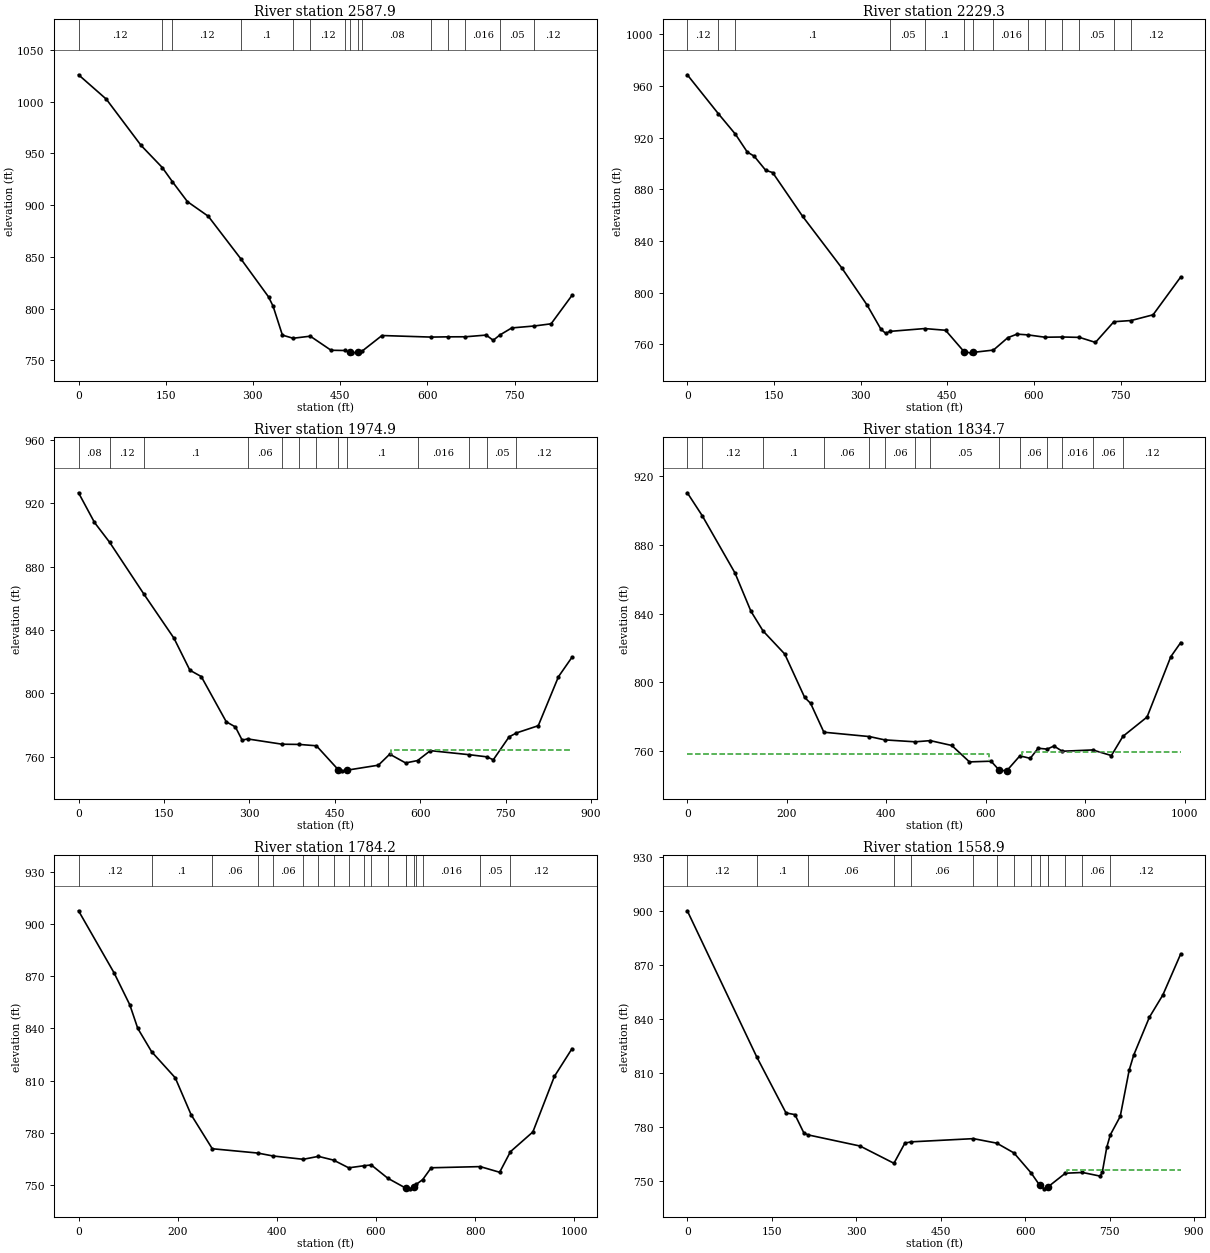
Type RM Length L Ch R = 1 ,2587.9  ,357.7,358.6,359.3
XS GIS Cut Line= 2
     1752658.302      370944.818     1752583.649      371790.304
#Sta/Elev= 30
       0 1026.05    47.8 1002.48   107.6  957.76  144.06936.4135  161.44922.7576
   187.3  903.46   223.2  889.32  280.05847.5472   326.8  811.44   334.7  802.38
   350.7  774.45     369  771.42  398.65773.4128   434.4   759.8  457.95759.5877
   466.3  757.87   470.2  757.32   481.3  758.22   487.6   758.9     522  774.06
   606.2772.5438  635.85  772.79   665.5  772.84   701.3  774.49   713.3  769.43
  724.81 774.586   745.2  781.39  784.11783.2777   812.9  785.38   848.8  812.82
#Mann= 15 ,-1 , 0
       0     .12       0  144.06     .08       0  161.44     .12       0
  280.05      .1       0     369     .05       0  398.65     .12       0
  457.95     .06       0   466.3    .045       0   481.3     .06       0
   487.6     .08       0   606.2    .016       0  635.85     .06       0
   665.5    .016       0  724.81     .05       0  784.11     .12       0
Bank Sta=466.3,481.3
XS Rating Curve= 0 ,0
Exp/Cntr=0.3,0.1

Type RM Length L Ch R = 1 ,2229.3  ,258.4,254.4,250.4
XS GIS Cut Line= 2
     1752326.705      370875.373     1752219.066      371722.595
#Sta/Elev= 30
       0  968.62   53.48938.6434   83.26922.6556   103.8  908.84   115.7  905.66
   135.7  894.72   147.7  892.96   199.5  859.15   267.4  819.16   311.3  790.36
   335.2   771.7   343.2  768.64  351.22770.1024  410.76772.2657     447  770.94
   479.5  754.11   490.9  753.48   494.5  753.82  529.85 755.622   554.7  765.22
   570.7  767.96   589.4 767.374  619.17765.5586  648.95765.7361  678.72  765.44
   706.4  761.55  738.27777.5605  768.04778.4788   806.1  782.91     854   812.2
#Mann= 14 ,-1 , 0
       0     .12       0   53.48     .08       0   83.26      .1       0
  351.22     .05       0  410.76      .1       0   479.5    .045       0
   494.5      .1       0  529.85    .016       0   589.4     .08       0
  619.17    .016       0  648.95     .06       0  678.72     .05       0
  738.27     .06       0  768.04     .12       0
Bank Sta=479.5,494.5
XS Rating Curve= 0 ,0
Exp/Cntr=0.3,0.1

Type RM Length L Ch R = 1 ,1974.9  ,162.4,140.2,118
XS GIS Cut Line= 4
     1752121.506      370816.062     1752031.445      371213.197
     1752039.041      371392.234     1751972.852      371664.586
#Sta/Elev= 30
       0  926.76      28  908.01   54.66895.4333  115.23 862.475   167.7  834.77
   195.6  814.56   215.6  810.55   259.5  781.94   275.5  778.71   287.4  770.35
  296.94 771.123  357.51767.7779   387.8 767.637  417.83 766.782   456.4  751.57
     463  750.94   471.4  751.35   526.7  754.52   546.6  761.48   574.5  755.94
  595.45757.4345     618  763.71  686.63 761.126  717.03759.8019   728.5  757.92
   756.2   772.4  769.26774.9172   807.5  779.48     843  810.48   866.7  822.75
#Mann= 13 ,-1 , 0
       0     .08       0   54.66     .12       0  115.23      .1       0
  296.94     .06       0  357.51     .05       0   387.8    .016       0
  417.83      .1       0   456.4    .045       0   471.4      .1       0
  595.45    .016       0  686.63     .06       0  717.03     .05       0
  769.26     .12       0
#XS Ineff= 2 , 0
                          549.02          763.85
Permanent Ineff=
       F       F
Bank Sta=456.4,471.4
XS Rating Curve= 0 ,0
Exp/Cntr=0.3,0.1

Type RM Length L Ch R = 1 ,1834.7  ,58.7,50.5,50.5
XS GIS Cut Line= 4
     1752006.703      370781.294     1751867.185      371306.555
     1752018.748      371398.742     1751953.318      371661.502
#Sta/Elev= 30
       0  910.25   30.01896.9251    95.9  863.57   127.9  841.35  152.25 829.892
   195.8  816.49   235.8  791.27   247.8  787.82  274.49771.0035  366.17768.4636
  396.73766.5438  457.85  765.42  488.41766.1046   531.5  763.29   567.1  753.74
   610.5  754.15   626.9  748.92   641.9  748.54   668.4757.2562   689.3   755.8
   705.1  761.69  723.21761.1667   736.8  762.96  753.65759.9324  814.52760.6932
   852.3  757.43   875.4 768.564     924  779.83   971.7  814.91   991.7  823.15
#Mann= 14 ,-1 , 0
       0     .08       0   30.01     .12       0  152.25      .1       0
  274.49     .06       0  366.17    .016       0  396.73     .06       0
  457.85      .1       0  488.41     .05       0   626.9    .045       0
   668.4     .06       0  723.21     .08       0  753.65    .016       0
  814.52     .06       0   875.4     .12       0
#XS Ineff= 2 , 0
          605.78  758.24  671.83          759.76
Permanent Ineff=
       F       F
Bank Sta=626.9,641.9
XS Rating Curve= 0 ,0
Exp/Cntr=0.3,0.1

Type RM Length L Ch R = 1 ,1784.2  ,187.5,225.4,254.9
XS GIS Cut Line= 4
     1751995.505      370785.982     1751843.748      371351.346
      1751995.31      371443.534     1751936.912      371668.794
#Sta/Elev= 30
       0  907.49    71.7  871.87   103.5  853.49   119.5     840   147.5 826.595
   195.1  811.64     227  790.52  269.83770.9236  361.57768.4457  392.15766.7797
  453.32 764.862   483.9766.5425  514.48764.3954  545.06759.9693  575.64761.1536
  590.56761.6137  624.12 753.961   659.7 748.388   660.3  748.31   668.2  747.91
     676  748.84  680.95750.4189  694.27753.1804   711.5     760  810.38760.6671
   849.6  757.42  871.41769.2488   916.6  780.55     960  812.41   995.5  828.31
#Mann= 19 ,-1 , 0
       0     .12       0   147.5      .1       0  269.83     .06       0
  361.57    .016       0  392.15     .06       0  453.32      .1       0
   483.9     .05       0  514.48      .1       0  545.06    .016       0
  575.64      .1       0  590.56    .016       0  624.12     .05       0
   659.7    .016       0   660.3    .045       0     676    .016       0
  680.95     .05       0  694.27    .016       0  810.38     .05       0
  871.41     .12       0
Bank Sta=660.3,676
XS Rating Curve= 0 ,0
Exp/Cntr=0.3,0.1

Type RM Length L Ch R = 1 ,1558.9  ,337.8,340.8,343.5
XS GIS Cut Line= 2
     1751853.444      370749.586     1751640.565      371599.886
#Sta/Elev= 30
       0  900.19  123.48818.9324   175.3  787.92   191.2  786.97   207.2  776.71
  214.83775.6951   306.8  769.53  367.06759.9451   386.5  771.14  397.51771.8433
  508.17773.6335  549.75771.1195   580.2 765.695  610.64754.6134   625.8  747.81
   633.5  745.75   640.8  746.89  641.09746.9273  671.54754.4258  701.99754.8412
   733.1  752.83   737.1  754.91   745.1  768.83  751.37775.7256     769  785.98
   784.9  811.67   792.9  819.99   820.8  841.05   844.7  853.42   876.5  876.27
#Mann= 15 ,-1 , 0
       0     .12       0  123.48      .1       0  214.83     .06       0
  367.06    .016       0  397.51     .06       0  508.17    .016       0
  549.75     .05       0   580.2      .1       0  610.64     .05       0
   625.8    .045       0   640.8     .05       0  641.09     .08       0
  671.54    .016       0  701.99     .06       0  751.37     .12       0
#XS Ineff= 2 , 0
                          673.89          756.11
Permanent Ineff=
       F       F
Bank Sta=625.8,640.8
XS Rating Curve= 0 ,0
Exp/Cntr=0.3,0.1

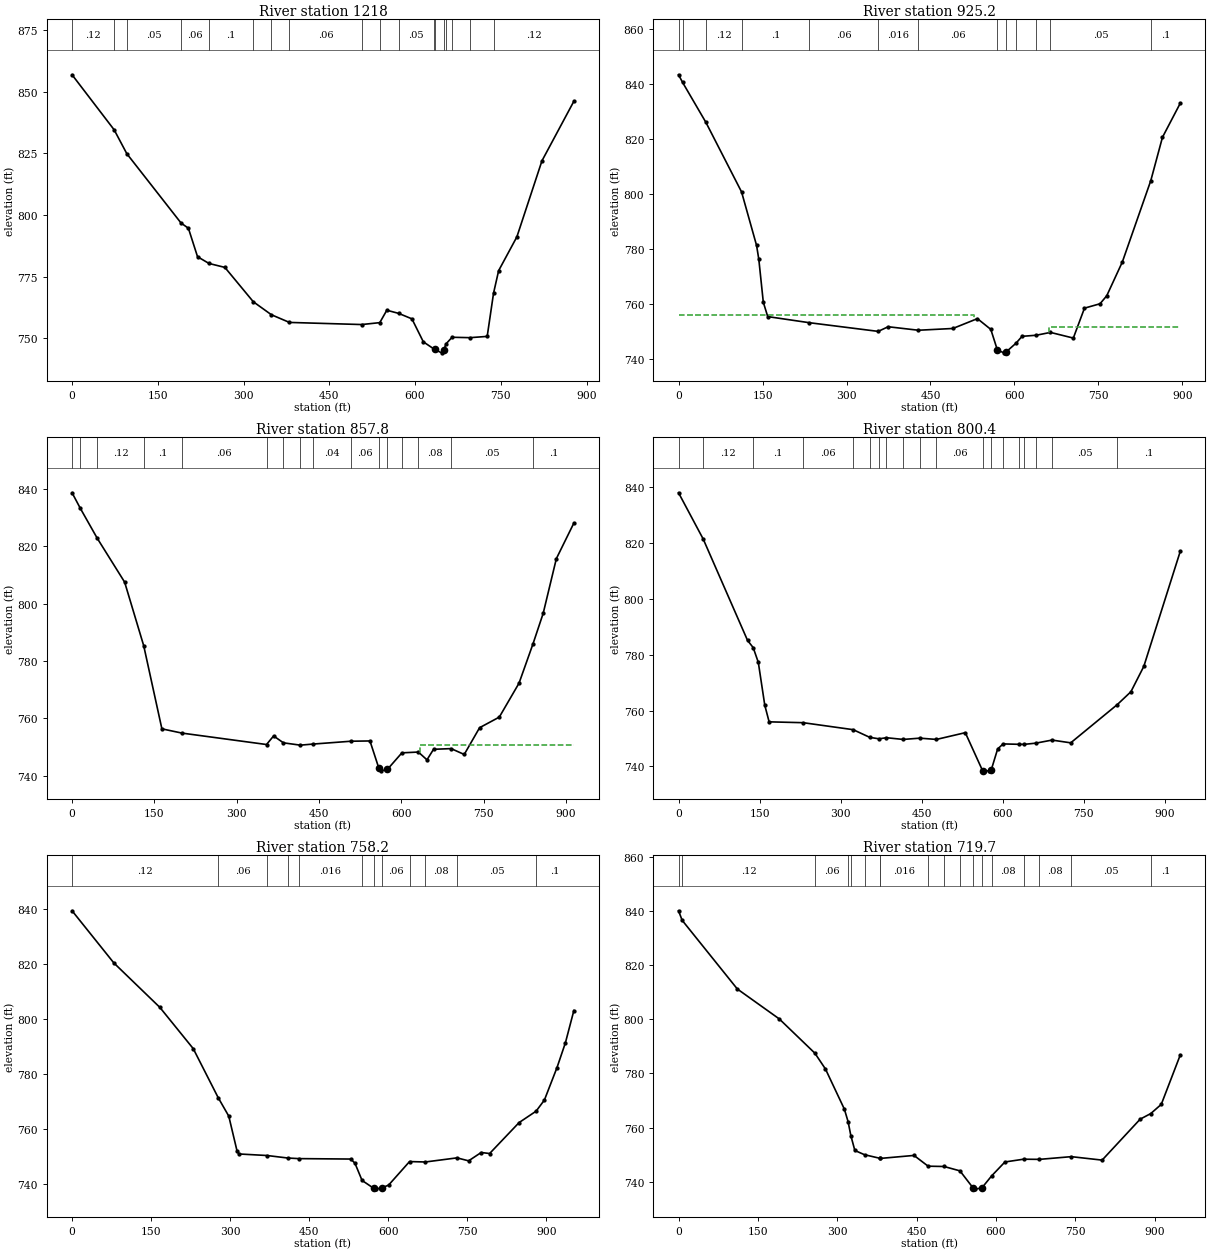
Type RM Length L Ch R = 1 ,1218    ,295.1,292.8,290.7
XS GIS Cut Line= 2
      1751608.55      370661.716      1751296.05      371482.028
#Sta/Elev= 30
       0  856.81   73.63834.5118    95.8  824.83  190.62796.7648   203.5  794.64
   219.5   783.1  239.55780.3774   267.3  778.78  317.05764.8591  348.65759.6065
  380.26756.4907  506.68755.6312  538.29756.4028   550.6  761.43  571.39760.1497
   594.5  757.94   614.5  748.62  633.11745.7216   634.4  745.57   646.4  744.17
   650.4   745.5  654.35747.8403  664.72 750.476  696.32750.3176   726.2  750.83
  737.31768.3447   746.2  777.46   778.1  791.14     822  821.96   877.8  846.07
#Mann= 18 ,-1 , 0
       0     .12       0   73.63     .06       0    95.8     .05       0
  190.62     .06       0  239.55      .1       0  317.05     .06       0
  348.65    .016       0  380.26     .06       0  506.68    .016       0
  538.29     .06       0  571.39     .05       0  633.11     .06       0
   634.4    .045       0   650.4     .06       0  654.35     .08       0
  664.72    .016       0  696.32     .06       0  737.31     .12       0
Bank Sta=634.4,650.4
XS Rating Curve= 0 ,0
Exp/Cntr=0.3,0.1

Type RM Length L Ch R = 1 ,925.2   ,67,67.4,67.6
XS GIS Cut Line= 3
     1751289.012      370556.672     1751101.295      371199.034
     1751133.847      371423.643
#Sta/Elev= 30
       0  843.42    7.26840.6393   48.86826.1184  112.55 800.826   139.4  781.34
   143.4  776.27   151.4   760.7   159.3  755.48  233.49753.2615  356.57750.1028
   374.4  751.79  428.41750.5184     490  751.16   533.8  754.74   557.7  750.83
   569.6  743.24   581.6   742.3   585.6  742.72  602.74745.8083   613.5   748.3
  638.98748.7033  664.28749.7305   705.1  747.67     725  758.55   752.8  760.15
   764.8  763.06   792.7  775.38   843.5804.9632   864.3  820.69   896.2  833.11
#Mann= 13 ,-1 , 0
       0     .12       0    7.26      .1       0   48.86     .12       0
  112.55      .1       0  233.49     .06       0  356.57    .016       0
  428.41     .06       0   569.6    .045       0   585.6     .05       0
  602.74    .016       0  638.98     .08       0  664.28     .05       0
   843.5      .1       0
#XS Ineff= 2 , 0
          528.38  756.22  662.54          751.55
Permanent Ineff=
       F       F
Bank Sta=569.6,585.6
XS Rating Curve= 0 ,0
Exp/Cntr=0.3,0.1

Type RM Length L Ch R = 1 ,857.8   ,57.7,57.4,57.6
XS GIS Cut Line= 3
     1751235.977      370530.029     1751062.366      371107.286
     1751109.353      371415.454
#Sta/Elev= 30
       0  838.61   15.11833.1626   45.95 822.724    95.8  807.46  130.57785.2863
   163.7  756.31  200.17754.8301  354.38 750.846   367.3  753.83  385.22 751.433
  416.07750.6213   438.2 750.989   508.6 751.996   542.9  752.09   558.9  742.71
   562.7  741.67   574.8   742.2  601.12747.9422  631.05748.2225   646.8  745.51
   658.8  749.18  690.81 749.418   714.7  747.38   742.7  756.71   778.6   760.4
   814.6  772.24  840.19786.0259   858.6  796.58   882.6  815.65   914.5  828.04
#Mann= 16 ,-1 , 0
       0     .12       0   15.11      .1       0   45.95     .12       0
  130.57      .1       0  200.17     .06       0  354.38     .04       0
  385.22    .016       0  416.07     .06       0   438.2     .04       0
   508.6     .06       0   558.9    .045       0   574.8     .06       0
  601.12    .016       0  631.05     .08       0  690.81     .05       0
  840.19      .1       0
#XS Ineff= 2 , 0
                          633.64          750.64
Permanent Ineff=
       F       F
Bank Sta=558.9,574.8
XS Rating Curve= 0 ,0
Exp/Cntr=0.3,0.1

Type RM Length L Ch R = 1 ,800.4   ,65.7,42.2,22.1
XS GIS Cut Line= 3
     1751187.149      370500.732     1751013.537      371077.989
     1751080.708      371397.225
#Sta/Elev= 30
       0  838.03   45.71821.4422   127.8  785.14  138.23782.5704   147.7  777.29
   159.7  761.91   167.7  755.99  230.76755.6837  323.29753.1849  354.13750.4243
  371.22749.9102  384.98750.3011  415.82749.6877  446.66750.1432   477.5749.6925
   530.9  752.11   562.9   738.5   574.8  738.44   578.8  738.67   590.8  746.28
  600.88748.0816   631.1747.9387  639.87747.9263  661.28748.3478  691.46749.4568
   726.1  748.47  812.19762.1507   837.5  766.77   861.4  775.85     929  817.13
#Mann= 19 ,-1 , 0
       0      .1       0   45.71     .12       0  138.23      .1       0
  230.76     .06       0  323.29     .05       0  354.13     .04       0
  371.22     .06       0  384.98     .04       0  415.82    .016       0
  446.66     .04       0   477.5     .06       0   562.9    .045       0
   578.8     .06       0  600.88    .016       0   631.1     .08       0
  639.87    .016       0  661.28     .08       0  691.46     .05       0
  812.19      .1       0
Bank Sta=562.9,578.8
XS Rating Curve= 0 ,0
Exp/Cntr=0.3,0.1

Type RM Length L Ch R = 1 ,758.2   ,33,38.5,37.2
XS GIS Cut Line= 3
     1751066.923      370460.801     1750950.603      370785.454
     1751058.572      371382.902
#Sta/Elev= 30
       0  839.24    79.3  820.27   166.5  804.13   229.9  789.12  277.16771.3241
   297.3  764.59   313.2  751.75   317.1  750.83  370.14750.2723  409.46749.3565
  430.17749.1461   528.6  748.99   536.6  747.51  550.22741.2044   572.4  738.34
   576.5  738.16   587.4   738.5   600.5  739.51  640.26748.0737  670.28 747.923
  730.31  749.42   752.3  748.34   776.2  751.37   792.2     751   848.1  762.25
  880.37766.3961   896.1  770.43     920  782.23     936  791.27     952  802.97
#Mann= 12 ,-1 , 0
       0     .12       0  277.16     .06       0  370.14    .016       0
  409.46     .06       0  430.17    .016       0  550.22     .06       0
   572.4    .045       0   587.4     .06       0  640.26    .016       0
  670.28     .08       0  730.31     .05       0  880.37      .1       0
Bank Sta=572.4,587.4
XS Rating Curve= 0 ,0
Exp/Cntr=0.3,0.1

Type RM Length L Ch R = 1 ,719.7   ,146.8,153.2,162.3
XS GIS Cut Line= 3
     1751041.923      370449.473     1750926.031      370774.565
     1751037.739      371367.277
#Sta/Elev= 30
       0     840    6.82836.4908   111.1  811.14   190.4  800.09  257.67787.4483
   277.7   781.6   313.4   766.8  320.39762.2126  325.71 756.969   333.2  751.55
  351.47749.9833  380.35  748.67  381.53748.6174     445  749.72  471.69745.7462
  501.75 745.636   531.8744.0242   556.8  737.69   560.8  737.39   572.8  737.63
  591.91742.2142   616.8   747.3  652.03748.3267  682.08748.2678  742.19749.2648
   800.5  747.99   872.4   763.1  892.47765.1749   912.3  768.56   948.3  786.84
#Mann= 18 ,-1 , 0
       0      .1       0    6.82     .12       0  257.67     .06       0
  320.39     .06       0  325.71     .06       0  351.47    .016       0
  380.35     .06       0  381.53    .016       0  471.69     .12       0
  501.75     .08       0   531.8    .016       0   556.8    .045       0
   572.8     .06       0  591.91     .08       0  652.03    .016       0
  682.08     .08       0  742.19     .05       0  892.47      .1       0
Bank Sta=556.8,572.8
XS Rating Curve= 0 ,0
Exp/Cntr=0.3,0.1

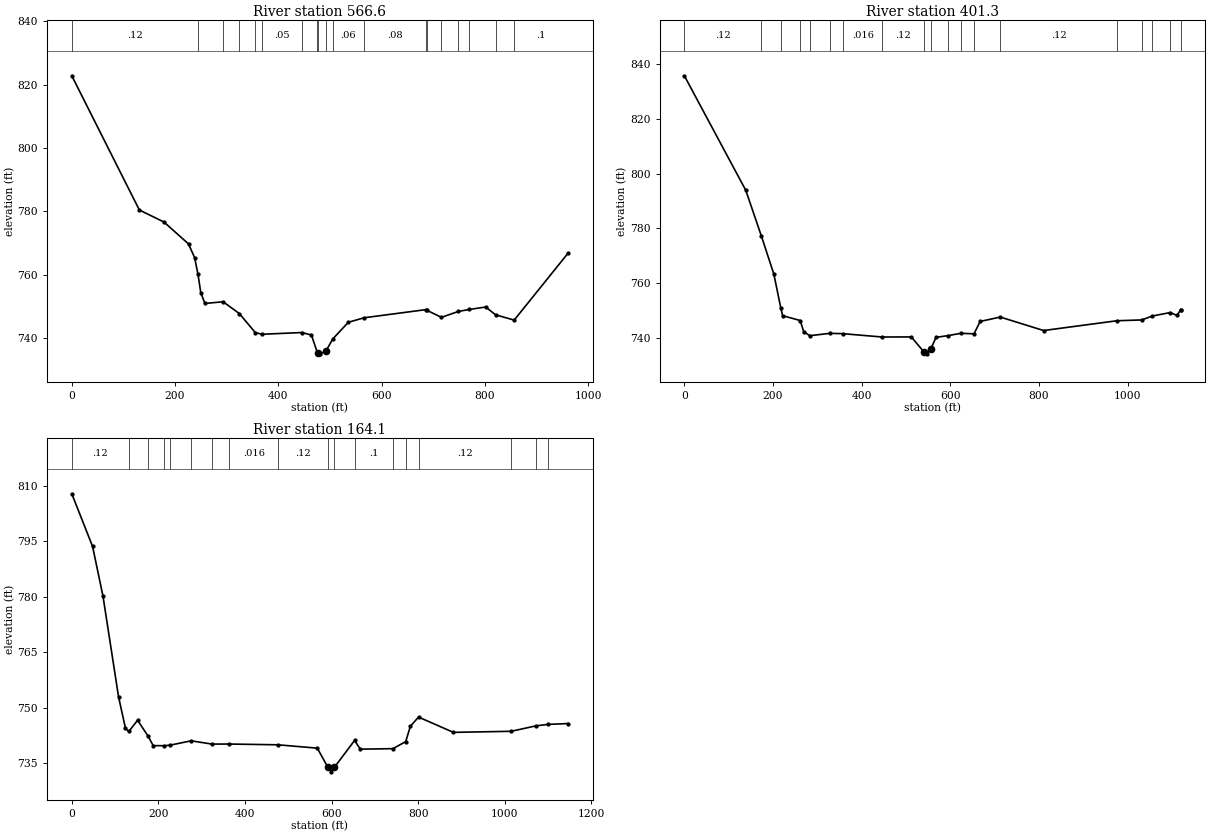
Type RM Length L Ch R = 1 ,566.6   ,158.4,165.3,171.8
XS GIS Cut Line= 4
     1750926.037      370445.567     1750810.145      370770.659
     1750882.167      371152.796     1751012.999      371338.631
#Sta/Elev= 30
       0  822.82   130.9   780.4   178.5  776.61   226.1  769.69     238  765.31
  244.48760.0726   249.9  754.26   257.9  750.87  293.18751.4047  324.54747.6824
  355.45741.6773  368.16741.1329  445.61741.6831   464.2  740.91  475.67735.3269
   476.1  735.17     480  734.95     492  735.75  505.73739.6908   535.6  744.91
  565.84746.3363  686.06748.9214  687.16748.7608  716.11746.4802  748.63748.3386
  770.24748.9753   801.8  749.75  820.87747.2898  856.99745.6122   961.3  766.75
#Mann= 19 ,-1 , 0
       0     .12       0  244.48    .016       0  293.18     .08       0
  324.54     .06       0  355.45     .12       0  368.16     .05       0
  445.61     .06       0  475.67     .12       0   476.1    .045       0
     492     .12       0  505.73     .06       0  565.84     .08       0
  686.06     .06       0  687.16     .08       0  716.11     .06       0
  748.63     .08       0  770.24    .016       0  820.87     .05       0
  856.99      .1       0
Bank Sta=476.1,492
XS Rating Curve= 0 ,0
Exp/Cntr=0.3,0.1

Type RM Length L Ch R = 1 ,401.3   ,237.9,237.1,236.7
XS GIS Cut Line= 4
      1750904.77       370397.39     1750694.701      370590.098
     1750668.659      371083.154     1750920.551       371312.59
#Sta/Elev= 30
       0  835.64   138.6  793.86  173.95777.1031   201.9  763.31  217.64750.9032
   221.7  748.16  261.33746.4041   269.2  742.35  282.95740.8646  328.16741.7237
  357.73741.5994  446.46 740.383     512  740.42   539.9  735.05   547.9  734.25
   555.9  736.03   567.8  740.27  594.35740.8814  623.92741.7373   653.5741.5573
   667.3  746.06  712.65747.6603   810.5  742.75  975.98746.3182 1031.59746.6096
 1055.89748.0387 1095.84   749.3  1111.6  748.24 1119.31750.3033  1119.5  750.37
#Mann= 19 ,-1 , 0
       0     .12       0  173.95     .08       0  217.64    .016       0
  261.33     .06       0  282.95    .016       0  328.16     .06       0
  357.73    .016       0  446.46     .12       0   539.9    .045       0
   555.9     .12       0  594.35     .06       0  623.92     .05       0
   653.5     .06       0  712.65     .12       0  975.98     .06       0
 1031.59     .08       0 1055.89    .016       0 1095.84     .05       0
 1119.31      .1       0
Bank Sta=539.9,555.9
XS Rating Curve= 0 ,0
Exp/Cntr=0.3,0.1

Type RM Length L Ch R = 1 ,164.1   ,148.9,164.1,179.1
XS GIS Cut Line= 4
     1750776.298      370374.821     1750451.645      370628.293
     1750441.228      371161.279     1750580.378      371306.505
#Sta/Elev= 30
       0  807.83      48  793.61      72  780.21     108     753     124  744.47
  131.77743.6496     152  746.68  176.49742.3285     188  739.82  213.96739.7912
  227.76  739.96  275.75741.1171  323.75740.2345  363.84 740.248   475.8740.0422
     567  739.14   591.4  733.98   598.9  732.74   606.4  733.94  653.05741.2106
   666.5  738.86  741.68 739.001  771.22740.8984   781.9  745.02  800.76747.5312
   881.3   743.4 1014.79  743.69 1072.52  745.17 1100.17745.5524  1146.1  745.78
#Mann= 18 ,-1 , 0
       0     .12       0  131.77    .016       0  176.49     .12       0
  213.96     .06       0  227.76    .016       0  275.75     .12       0
  323.75     .06       0  363.84    .016       0   475.8     .12       0
   591.4    .045       0   606.4     .12       0  653.05      .1       0
  741.68     .05       0  771.22     .06       0  800.76     .12       0
 1014.79     .08       0 1072.52     .06       0 1100.17     .12       0
Bank Sta=591.4,606.4
XS Rating Curve= 0 ,0
Exp/Cntr=0.3,0.1

Chan Stop Cuts=-1
Use User Specified Reach Order=0
Composite Channel Slope=5